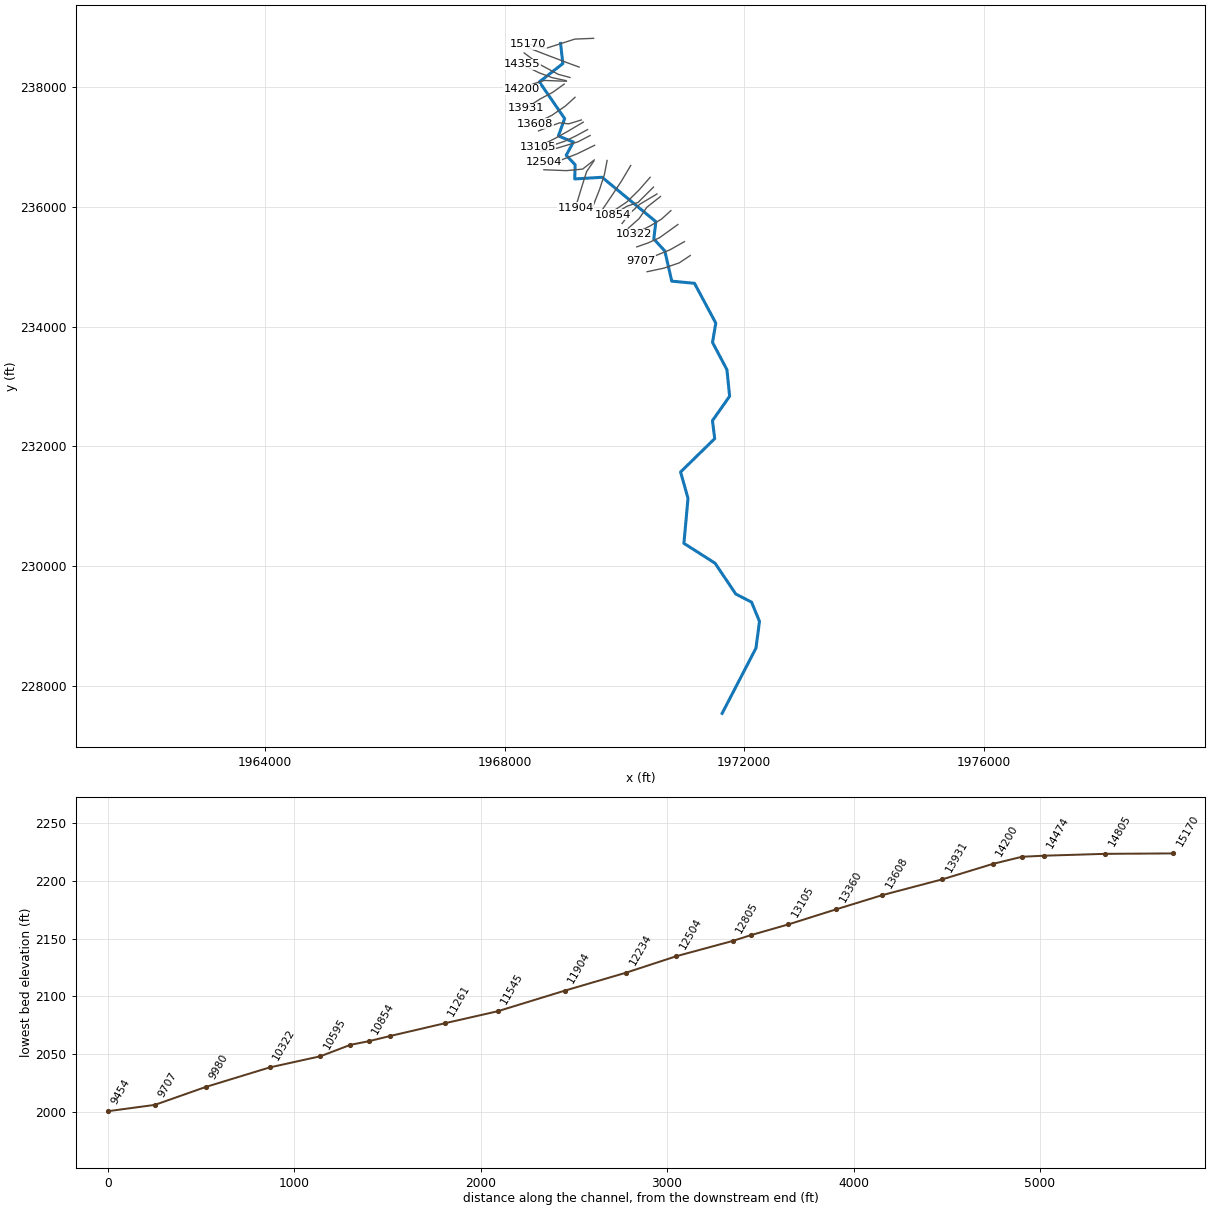
--- PRKRCK.prj (project) ---

Proj Title=PRKRCK
Current Plan=p01
Default Exp/Contr=0,0
English Units
Geom File=g01
Flow File=f01
Plan File=p01
BEGIN DESCRIPTION:
Stream Name: Parker Creek
Flood Zone: Approximate
Summers County, West Virginia
HEC-RAS Version: 5.0.7
Hydrology Method:
Regression.
Model Notes:
END DESCRIPTION:
DSS Export Rating Curves= 0
DSS Export Rating Curve Sorted= 0
DSS Export Volume Flow Curves= 0
DXF OffsetX= 0
DXF OffsetY= 0
DXF ScaleX= 0
DXF ScaleY= 0

--- PRKRCK.p01 (plan) ---

Plan Title=Floodplain
Program Version=5.07
Short Identifier=Floodplain
Geom File=g01
Flow File=f01
Subcritical Flow
K Sum by GR= 0
Std Step Tol= 0.01
Critical Tol= 0.01
Num of Std Step Trials= 20
Max Error Tol= 0.3
Flow Tol Ratio= 0.001
Split Flow NTrial= 30
Split Flow Tol= 0.02
Split Flow Ratio= 0.02
Log Output Level= 0
Friction Slope Method= 1
Unsteady Friction Slope Method= 2
Unsteady Bridges Friction Slope Method= 1
Parabolic Critical Depth
Global Vel Dist= 0 , 0 , 0
Global Log Level= 0
CheckData=True
Encroach Param=-1 ,0,0, 0
Mapping Interval=1HOUR
Computation Time Step Use Courant=        0
Computation Time Step Use Time Series=    0
Computation Time Step Count To Double=0
Computation Time Step Max Doubling=0
Computation Time Step Max Halving=0
Computation Time Step Residence Courant=0
Run HTab= 0
Run UNet= 0
Run Sediment= 0
Run PostProcess= 0
Run WQNet= 0
Run RASMapper= 0
UNET Theta= 0
UNET Theta Warmup= 0
UNET ZTol= 0
UNET ZSATol= 0
UNET MxIter= 0
UNET Max Iter WO Improvement= 0
UNET MaxInSteps= 0
UNET DtIC= 0
UNET DtMin= 0
UNET MaxCRTS= 0
UNET WFStab= 0
UNET SFStab= 0
UNET WFX= 1
UNET SFX= 1
UNET 1D Methodology=Finite Difference
UNET DSS MLevel= 1
UNET Pardiso=0
UNET DZMax Abort= 0
UNET Use Existing IB Tables= 0
UNET Froude Reduction=False
UNET Froude Limit= 0
UNET Froude Power= 0
UNET D1 Cores= 0
UNET D2 Coriolis=0
UNET D2 Cores= 0
UNET D2 Theta= 1
UNET D2 Theta Warmup= 1
UNET D2 Z Tol= 0.01
UNET D2 Volume Tol= 0.01
UNET D2 Max Iterations= 20
UNET D2 Equation= 0
UNET D2 RampUpFraction=0.1
UNET D2 TimeSlices= 1
UNET D2 BCVolumeCheck=0
UNET D1D2 MaxIter= 0
UNET D1D2 ZTol=0.01
UNET D1D2 QTol=0.1
UNET D1D2 MinQTol=1
Write IC File= 0
Write IC File at Fixed DateTime=0
Write IC File at Sim End=0
Echo Input=False
Echo Parameters=False
Echo Output=False
Write Detailed= 0
HDF Write Warmup=0
HDF Write Time Slices=0
HDF Flush=0
HDF Face Node Velocities=0
HDF Compression= 1
HDF Chunk Size= 1
HDF Spatial Parts= 1
HDF Use Max Rows=0
HDF Fixed Rows= 1
Calibration Method= 0
Calibration Iterations= 20
Calibration Max Change=0.05
Calibration Tolerance=0.2
Calibration Maximum=1.5
Calibration Minimum=0.5
Calibration Optimization Method= 1
WQ AD Non Conservative
WQ ULTIMATE=-1
WQ Max Comp Step=1HOUR
WQ Output Interval=15MIN
WQ Output Selected Increments= 0
WQ Output face flow=0
WQ Output face velocity=0
WQ Output face area=0
WQ Output face dispersion=0
WQ Output cell volume=0
WQ Output cell surface area=0
WQ Output cell continuity=0
WQ Output cumulative cell continuity=0
WQ Output face conc=0
WQ Output face dconc_dx=0
WQ Output face courant=0
WQ Output face peclet=0
WQ Output face adv mass=0
WQ Output face disp mass=0
WQ Output cell mass=0
WQ Output cell source sink temp=0
WQ Output nsm pathways=0
WQ Output nsm derived pathways=0
WQ Output MaxMinRange=-1
WQ Daily Max Min Mean=-1
WQ Daily Range=0
WQ Daily Time=0
WQ Create Restart=0
WQ Fixed Restart=0
WQ System Summary=0
WQ Write To DSS=0
WQ Use Fixed Temperature=0
Sorting and Armoring Iterations= 10
XS Update Threshold= 0.02
Bed Roughness Predictor= 0
Hydraulics Update Threshold= 0.02
Energy Slope Method= 1
Volume Change Method= 1
Sediment Retention Method= 0
XS Weighting Method= 0
Number of US Weighted Cross Sections= 1
Number of DS Weighted Cross Sections= 1
Upstream XS Weight=0
Main XS Weight=1
Downstream XS Weight=0
Number of DS XS's Weighted with US Boundary= 1
Upstream Boundary Weight= 1
Weight of XSs Associated with US Boundary= 0
Number of US XS's Weighted with DS Boundary= 1
Downstream Boundary Weight= 0.5
Weight of XSs Associated with DS Boundary= 0.5
Percentile Method= 0
Sediment Output Level= 3
Mass or Volume Output= 0
Output Increment Type= 1
Profile and TS Output Increment= 1
XS Output Flag= 0
XS Output Increment= 10
Write Gradation File= 0
Read Gradation Hotstart= 0
Write HDF5 File= 1
Write Binary Output= 1
Write DSS Sediment File= 0
SV Curve= 0
Specific Gage Flag= 0

--- PRKRCK.f01 (steady flow) ---

Flow Title=Flows
Program Version=5.07
Number of Profiles= 6
Profile Names=01pct,10pct,04pct,02pct,0_2pct,01plus
River Rch & RM=PRKRCK,Main            ,15170
     717     382     506     608     998    1061
River Rch & RM=PRKRCK,Main            ,11904
     801     429     566     680    1111    1184
River Rch & RM=PRKRCK,Main            ,10595
     899     484     638     764    1246    1330
River Rch & RM=PRKRCK,Main            ,5112
    1014     548     721     863    1401    1500
River Rch & RM=PRKRCK,Main            ,1703
    2050    1138    1478    1755    2796    3032
River Rch & RM=PRKRCK,Main            ,25
    3673    2086    2679    3161    4955    5433
Boundary for River Rch & Prof#=PRKRCK,Main            , 1
Up Type= 0
Dn Type= 1
Dn Known WS=1705.6
Boundary for River Rch & Prof#=PRKRCK,Main            , 2
Up Type= 0
Dn Type= 1
Dn Known WS=1704.2
Boundary for River Rch & Prof#=PRKRCK,Main            , 3
Up Type= 0
Dn Type= 1
Dn Known WS=1704.9
Boundary for River Rch & Prof#=PRKRCK,Main            , 4
Up Type= 0
Dn Type= 1
Dn Known WS=1705.2
Boundary for River Rch & Prof#=PRKRCK,Main            , 5
Up Type= 0
Dn Type= 1
Dn Known WS=1706.3
Boundary for River Rch & Prof#=PRKRCK,Main            , 6
Up Type= 0
Dn Type= 1
Dn Known WS=1706.6
DSS Import GetInterval= 0
DSS Import GetPeak= 0
DSS Import FillOption= 0

--- PRKRCK.g01 (geometry) ---

Geom Title=Geometry
Program Version=5.07

River Reach=PRKRCK          ,Main
Reach XY= 30
1968935.51800001 238730.048000011968973.09400002238393.722999998
1968581.85299999238087.4250000051969003.16500001237475.170999996
1968898.97199999237185.1210000571969149.21400001237082.564000007
1969029.45799999236862.385000007     1969178.381236703.397000047
     1969171.501236467.0899999991969628.38100001236494.370000001
1970524.90800001235753.3970000291970490.88100001235463.813999986
     1970674.458235263.2230000191970790.18600001234759.647000041
1971169.35300001234723.536000017     1971525.031234058.366000022
1971470.04699999233736.7300000281971710.86800002233280.191000021
     1971755.464232837.4250000141971468.98200002232430.048000025
     1971506.853232129.7859999691970937.40800002231572.146999977
1971061.01900001231132.5640000271970992.80000002230380.515000015
     1971512.582230048.710000023     1971858.068229533.953000028
1972121.08900002229398.536000027     1972253.902229076.486999994
     1972194.874228630.3070000131971630.41999999227540.564999981

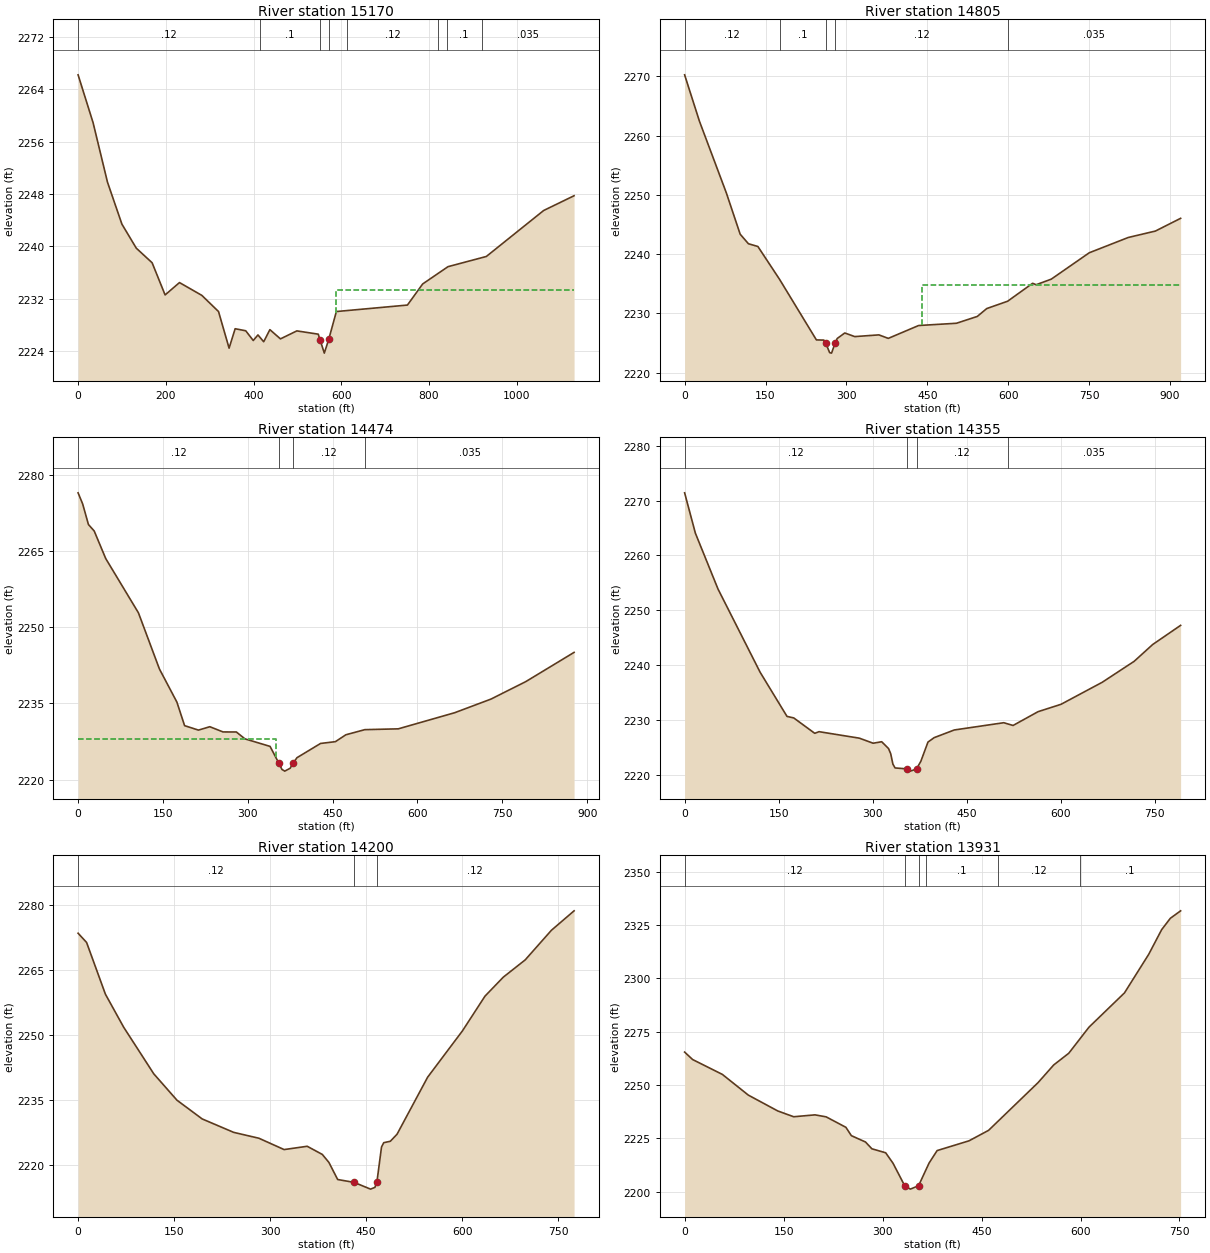
Type RM Length L Ch R = 1 ,15170   ,374.7,364.6,351.8
XS GIS Cut Line= 4
1969486.54515176238815.2521280061969173.14587008238802.563897978
1968690.99312904238647.7674916421968387.74443138238716.283933791
#Sta/Elev= 30
       0 2266.22    34.2  2258.9      67 2249.81    99.9 2243.39   132.7 2239.71
   168.8 2237.48   198.4 2232.56   231.2 2234.45   282.2 2232.49   320.2 2230.02
   344.3 2224.42   358.1 2227.39   382.2 2227.08   399.4 2225.59   410.1 2226.44
   423.2  2225.4   437.3 2227.25   461.4 2225.84   498.8 2227.06   547.6 2226.56
  551.52 2225.74   561.4 2223.66   571.5 2225.77   588.9 2230.02   750.9 2231.01
   785.7 2234.24   843.4 2236.88   930.8 2238.44  1061.5 2245.47  1130.9 2247.73
#Mann= 8 ,-1 , 0
       0     .12       0  413.66      .1       0  551.52    .045       0
   571.5      .1       0  613.66     .12       0  820.05    .035       0
  840.05      .1       0  920.05    .035       0
#XS Ineff= 2 , 0
                          587.97         2233.25
Permanent Ineff=
       F       F
Bank Sta=551.52,571.5
XS Rating Curve= 0 ,0
Exp/Cntr(USF)=0,0
Exp/Cntr=0.3,0.1

Type RM Length L Ch R = 1 ,14805   ,325.7,331.1,329
XS GIS Cut Line= 4
1969245.31763726238335.1720191861969062.67279106238401.783668977
1968716.72196472238532.8582056641968385.81247866238661.783979454
#Sta/Elev= 30
       0 2270.26    27.6  2262.4    77.4 2250.32     103 2243.36   118.3 2241.75
   135.8 2241.29   175.9 2235.76   244.3 2225.52   258.3 2225.49   261.3 2225.04
   268.9 2223.37   272.4 2223.29   279.1 2225.01   282.9 2225.76   296.9 2226.69
   315.4 2226.08   360.1 2226.37   377.6 2225.78   433.8 2227.95   503.9 2228.33
   542.5 2229.48   560.1 2230.81   598.8 2232.05   645.2 2235.08   651.6 2234.83
   679.8 2235.78   750.2 2240.23   822.5 2242.81   872.7 2243.89   919.5 2246.04
#Mann= 5 ,-1 , 0
       0     .12       0   175.9      .1       0   261.3    .045       0
   279.1     .12       0   598.8    .035       0
#XS Ineff= 2 , 0
       0                     440       0 2234.83
Permanent Ineff=
       F       F
Bank Sta=261.3,279.1
XS Rating Curve= 0 ,0
Exp/Cntr(USF)=0,0
Exp/Cntr=0.3,0.1

Type RM Length L Ch R = 1 ,14474   ,110.7,117,120.4
XS GIS Cut Line= 4
1969092.75547161238161.1222245691968895.06928513238214.841296981
1968570.60608776238388.8910915981968327.79588045238571.535937801
#Sta/Elev= 30
       0 2276.55     8.1 2274.36    18.3  2270.3    28.5 2269.02    48.9 2263.58
   106.7 2252.88   143.8 2241.81   174.7 2235.27   188.3 2230.63   212.8 2229.75
   232.9 2230.42   256.2 2229.39   279.8 2229.38   294.9 2228.03   339.4 2226.54
  354.962223.224   360.4    2222   365.4 2221.66   374.9 2222.22  379.972223.223
     387 2224.31   428.7 2227.12   454.9 2227.47   473.4 2228.83   506.9 2229.84
   566.1    2230   665.8 2233.18     730 2235.87   791.6 2239.32   876.9 2245.08
#Mann= 4 ,-1 , 0
       0     .12       0  354.96    .045       0  379.97     .12       0
   506.9    .035       0
#XS Ineff= 2 , 0
       0     350    2228               0
Permanent Ineff=
       F       F
Bank Sta=354.96,379.97
XS Rating Curve= 0 ,0
Exp/Cntr(USF)=0,0
Exp/Cntr=0.3,0.1

Type RM Length L Ch R = 1 ,14355   ,134.2,156.9,170.9
XS GIS Cut Line= 4
1969025.49263481238108.8713134021968792.90887791238159.224497885
1968579.50728653238238.350930643 1968286.9792624238382.217172022
#Sta/Elev= 30
       0  2271.4    17.2 2264.05    53.3 2253.89   120.5 2238.75   163.4 2230.71
   174.2 2230.43   207.7 2227.63   214.5 2227.93   278.8 2226.75   300.9 2225.83
   314.5  2226.1   325.4 2224.87   328.9 2223.93   332.4 2222.03   335.9 2221.33
  354.54 2221.16   360.3 2220.75   370.1 2221.14     377 2222.54   388.4 2226.04
   398.4 2226.85   430.4 2228.24   509.3 2229.56   524.2 2229.06   564.1 2231.57
   600.7 2232.91   666.5 2236.92   717.4 2240.73     747 2243.79   791.6 2247.28
#Mann= 4 ,-1 , 0
       0     .12       0  354.54    .045       0   370.1     .12       0
  515.57    .035       0
Bank Sta=354.54,370.1
XS Rating Curve= 0 ,0
Exp/Cntr(USF)=0,0
Exp/Cntr=0.3,0.1

Type RM Length L Ch R = 1 ,14200   ,261.1,269.5,271.6
XS GIS Cut Line= 4
1969032.59011051 238098.80810057 1968665.1516552238111.700677949
1968495.39938638238060.1303684331968284.82062252237967.733563884
#Sta/Elev= 30
       0 2273.41    13.3 2271.28    42.7 2259.38    71.2 2251.79   118.3 2241.05
   154.5 2234.99   193.9 2230.68   243.1 2227.59   282.5 2226.24   321.9 2223.63
     358 2224.39   381.6 2222.51   391.9 2220.68   405.6 2216.74  431.222216.086
     457 2214.53   463.9 2214.94  466.322216.085   467.3  2216.6   474.1 2224.21
   477.6 2225.22   487.9 2225.54   498.4 2227.17   546.2 2240.29   600.6 2250.95
   635.8 2258.93   664.4  2263.3   698.6 2267.27   739.6 2274.09     775 2278.56
#Mann= 3 ,-1 , 0
       0     .12       0  431.22    .045       0  466.32     .12       0
Bank Sta=431.22,466.32
XS Rating Curve= 0 ,0
Exp/Cntr(USF)=0,0
Exp/Cntr=0.3,0.1

Type RM Length L Ch R = 1 ,13931   ,320,322.5,324.5
XS GIS Cut Line= 4
1968996.06114126238051.5353168471968804.82124348237914.014491471
1968589.94495383237800.130057956 1968362.1760868237649.716655201
#Sta/Elev= 30
       0 2265.48    12.2 2261.98    57.2 2255.02    96.6 2245.31   141.1  2237.9
   165.3 2235.17   197.6 2236.06   214.5 2235.12   244.4 2230.23   252.7 2226.31
   274.1 2223.35   283.8 2220.15   304.7 2218.29   315.9 2213.36   333.52202.849
   342.1 2201.25  354.58 2202.85   370.5 2213.48   382.7 2219.32     431 2223.89
   460.7 2228.81   535.6 2251.15   559.4 2259.46   582.2 2264.94   612.9 2277.18
   666.6 2293.22   703.4 2311.33     723 2322.88   736.1 2328.18   751.7 2331.69
#Mann= 6 ,-1 , 0
       0     .12       0   333.5    .045       0  354.58     .12       0
  365.55      .1       0  475.55     .12       0  598.74      .1       0
Bank Sta=333.5,354.58
XS Rating Curve= 0 ,0
Exp/Cntr(USF)=0,0
Exp/Cntr=0.3,0.1

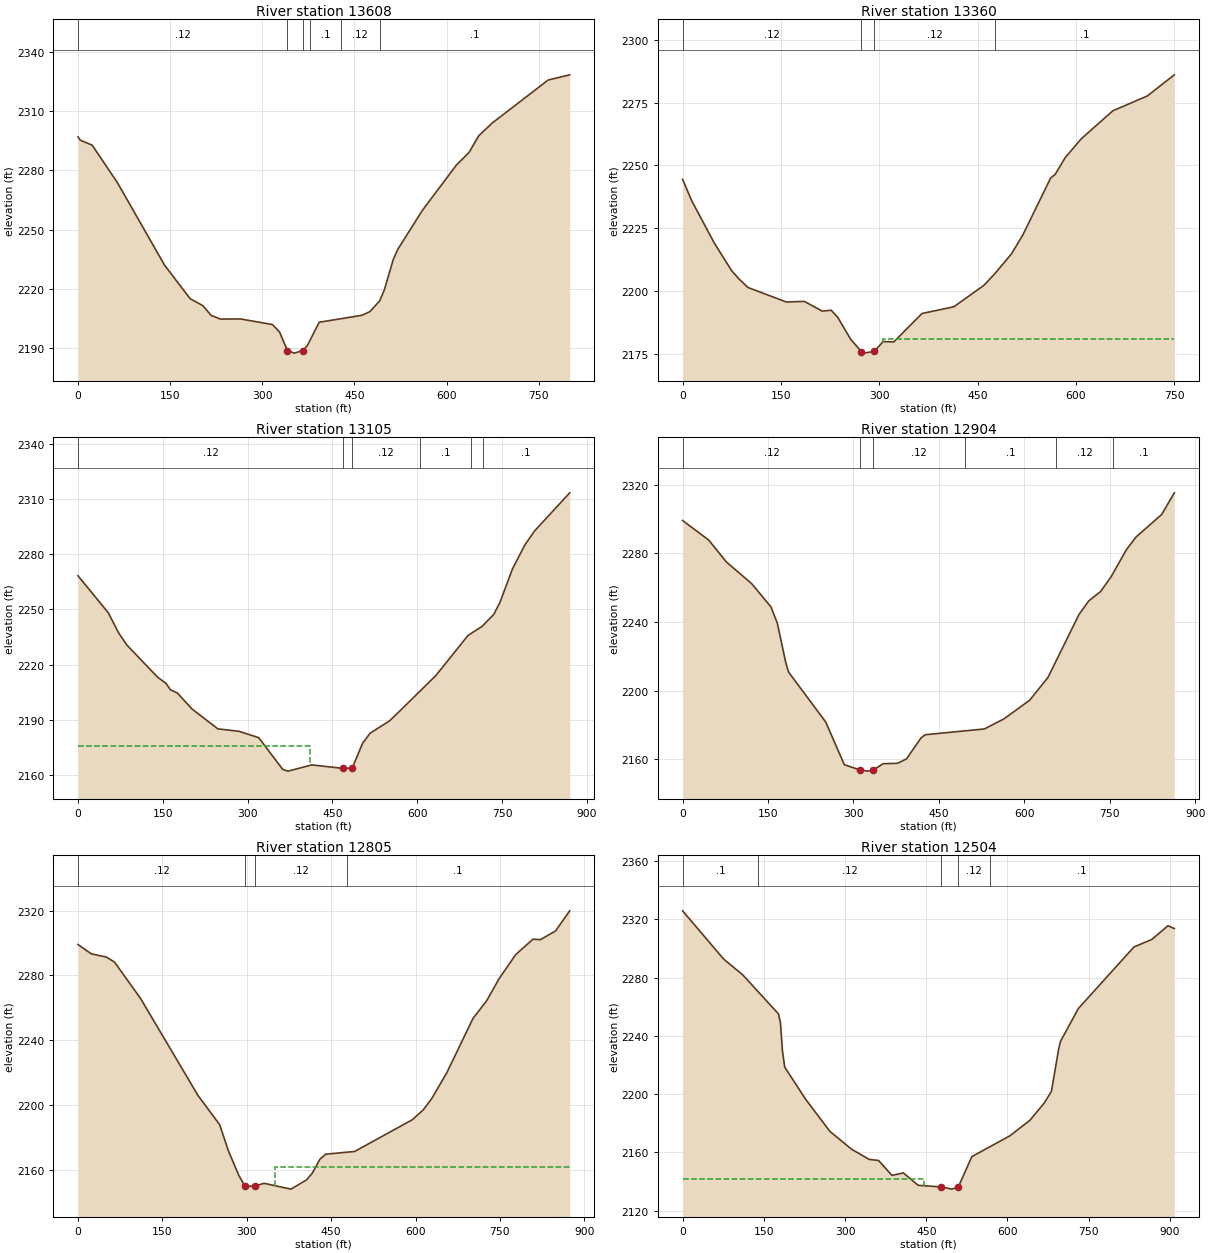
Type RM Length L Ch R = 1 ,13608   ,262.8,248.5,232.8
XS GIS Cut Line= 4
1969176.55722457237830.2127385071969015.40000733237684.096861545
 1968789.7799032237529.3859329971968512.58948955237391.865107621
#Sta/Elev= 30
       0 2296.97     3.8 2295.33    23.1  2292.8    64.2 2273.84   140.9  2232.1
   182.7 2215.08   203.4 2211.56   216.7 2206.67   231.7  2204.8   264.7 2204.86
   316.6 2202.03   328.2 2198.23   340.92188.862     352 2187.56  365.732188.861
   373.3 2191.31   392.6 2203.18   462.3 2206.71   475.4 2208.61   491.1    2214
   498.6 2219.49   513.2 2234.89   520.6 2240.07   560.8 2259.87   616.1 2282.77
   636.6 2289.09   652.4 2297.57   674.4 2304.02   765.4 2325.77   800.5 2328.41
#Mann= 6 ,-1 , 0
       0     .12       0   340.9    .045       0  365.73     .12       0
  377.54      .1       0  427.54     .12       0   491.1      .1       0
Bank Sta=340.9,365.73
XS Rating Curve= 0 ,0
Exp/Cntr(USF)=0,0
Exp/Cntr=0.3,0.1

Type RM Length L Ch R = 1 ,13360   ,247.6,255.1,266.4
XS GIS Cut Line= 4
 1969282.0540986237451.8821444391969071.05027791237387.142335818
1968917.59295377237403.9267306461968567.51843309237269.651572026
#Sta/Elev= 30
       0 2244.46      14 2235.87    48.3 2219.08    74.8 2208.08    86.1 2204.73
    99.8 2201.36   158.2 2195.59   185.6 2195.84   213.1 2191.95   226.6 2192.32
   236.5 2189.52   256.3 2180.75   272.8  2175.8   276.1 2175.22   292.5 2175.93
   305.8 2179.81   322.3 2179.71   365.2 2191.02   413.7 2193.68   459.4 2202.19
   476.1 2206.82   501.6 2214.77   518.8 2222.21   561.3 2244.95   568.3 2246.44
   583.8 2253.18   608.2 2260.64   656.2 2271.75   708.9 2277.68     750 2286.09
#Mann= 4 ,-1 , 0
       0     .12       0   272.8    .045       0   292.5     .12       0
   476.1      .1       0
#XS Ineff= 2 , 0
       0                  305.09       0    2181
Permanent Ineff=
       F       F
Bank Sta=272.8,292.5
XS Rating Curve= 0 ,0
Exp/Cntr(USF)=0,0
Exp/Cntr=0.3,0.1

Type RM Length L Ch R = 1 ,13105   ,203.6,201,196.5
XS GIS Cut Line= 4
1969314.07804995237415.5014994821969049.78021368237258.641808038
1968832.75516113237138.3110858331968551.26722169236998.641497561
#Sta/Elev= 30
       0 2268.32    53.5 2248.25    72.2 2237.13    86.6 2230.66   140.6  2213.3
   155.8 2209.85   163.5 2206.42   175.6  2204.7   201.6 2195.99   247.4 2185.18
   284.9 2183.85   319.7 2180.39   362.3  2163.1   371.6 2162.23   413.5 2165.61
   468.5 2163.72  485.092163.956   503.5 2177.41   516.8 2182.87   550.6 2189.43
   565.2 2193.69   632.9 2214.11     690 2235.95   714.5 2240.77   735.5 2247.37
   746.5 2253.97   768.4 2271.99   790.4 2285.04   807.5 2292.61   869.7 2313.34
#Mann= 6 ,-1 , 0
       0     .12       0   468.5    .045       0  485.09     .12       0
  605.49      .1       0  695.49     .12       0  715.49      .1       0
#XS Ineff= 2 , 0
          409.74 2175.89
Permanent Ineff=
       F       F
Bank Sta=468.5,485.09
XS Rating Curve= 0 ,0
Exp/Cntr(USF)=0,0
Exp/Cntr=0.3,0.1

Type RM Length L Ch R = 1 ,12904   ,99.4,98.5,98.5
XS GIS Cut Line= 4
1969385.15823826237291.2315082321969195.73435377237188.127368577
1969006.31046929237097.0120823711968591.49613998236957.941382371
#Sta/Elev= 30
       0 2299.21    45.8 2287.81    76.6  2275.1   121.4  2262.3   155.1 2248.79
   166.3 2239.32   181.4 2215.94   186.1 2210.74   251.3  2181.6     284  2156.7
   312.2 2153.55   325.8 2152.95     335 2153.59     352 2157.28   377.4 2157.51
   393.2 2160.11   418.7 2172.37     426 2174.19   529.8 2177.55   564.4 2183.47
   609.4 2194.32   641.7 2207.71   695.9 2244.27   713.2 2252.31     734 2257.75
   752.8  2266.6     779 2282.04   796.3 2289.62   841.2  2302.7   863.4 2315.36
#Mann= 6 ,-1 , 0
       0     .12       0   312.2    .045       0     335     .12       0
  495.86      .1       0  655.86     .12       0  755.86      .1       0
Bank Sta=312.2,335
XS Rating Curve= 0 ,0
Exp/Cntr(USF)=0,0
Exp/Cntr=0.3,0.1

Type RM Length L Ch R = 1 ,12805   ,279.9,301.2,295.7
XS GIS Cut Line= 4
1969427.96248346237192.0301582461969225.97877119237086.740776317
 1968849.9452643236972.8563428031968600.68876831236927.732321976
#Sta/Elev= 30
       0 2299.02    23.7 2293.25    50.2  2291.3      65 2288.14   111.3 2265.62
   213.4  2205.7   251.8 2187.74   267.5 2171.43     286 2156.27   296.9 2149.71
  314.51 2149.76   330.6 2151.51   378.6  2147.9     406 2153.57   416.3 2157.68
     430 2166.36   440.3 2169.48   491.7 2171.16   594.6 2190.84   613.9 2196.95
   628.8 2203.85   655.3 2219.63     702 2253.27   726.5 2264.36   748.6 2277.96
   778.1  2292.8   808.7  2302.3     822 2302.05   848.7 2307.35     874 2319.83
#Mann= 4 ,-1 , 0
       0     .12       0   296.9    .045       0  314.51     .12       0
  477.78      .1       0
#XS Ineff= 2 , 0
                          349.57         2161.85
Permanent Ineff=
       F       F
Bank Sta=296.9,314.51
XS Rating Curve= 0 ,0
Exp/Cntr(USF)=0,0
Exp/Cntr=0.3,0.1

Type RM Length L Ch R = 1 ,12504   ,270.2,269.6,257.4
XS GIS Cut Line= 4
1969503.16918484237028.7241781121969208.78866802236884.757064046
1968940.19330596236781.6164450141968650.11031493236742.938712877
#Sta/Elev= 30
       0 2325.86    75.8 2292.71   111.3 2281.81   177.1 2255.05   180.7 2248.88
   184.4 2229.68   188.6 2218.48   227.2 2196.48     272  2174.4   312.2 2162.11
   344.4 2155.18     362 2154.39   386.6 2144.19   407.7 2145.87   435.1 2137.37
     478 2136.24   497.4 2134.74   509.22136.198   534.1 2157.05   604.5 2171.36
   641.7 2182.12     668 2193.96   681.2 2201.94   694.5 2230.91   697.8 2236.14
   730.9 2258.77   833.5 2301.02   866.6 2306.21   896.4 2315.63   908.1 2313.71
#Mann= 5 ,-1 , 0
       0      .1       0     140     .12       0     478    .045       0
   509.2     .12       0   567.7      .1       0
#XS Ineff= 2 , 0
          446.54 2141.69
Permanent Ineff=
       F       F
Bank Sta=478,509.2
XS Rating Curve= 0 ,0
Exp/Cntr(USF)=0,0
Exp/Cntr=0.3,0.1

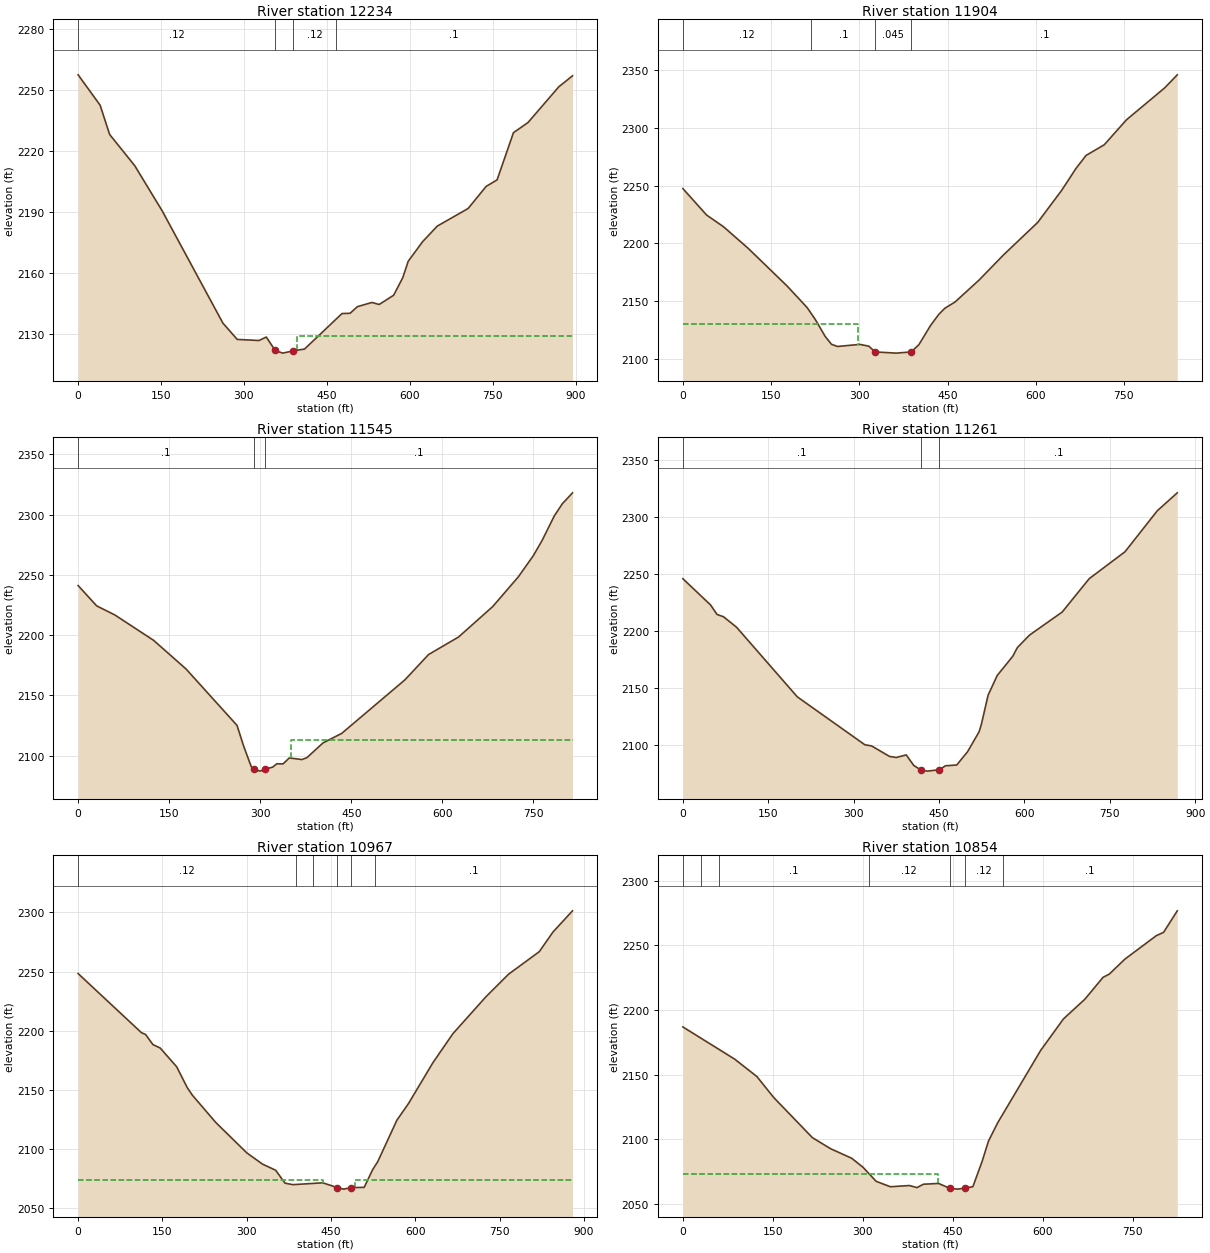
Type RM Length L Ch R = 1 ,12234   ,304.5,329.8,367.8
XS GIS Cut Line= 4
1969496.72289615 236783.765207911969303.33423546236631.203042259
1969032.59011051236605.4178875011968656.55660362236620.459227776
#Sta/Elev= 30
       0 2257.42    39.8 2242.47      57 2228.08   102.5 2212.69   152.4 2190.34
     262 2135.23   287.9 2127.22   327.3 2126.69   340.5 2128.39  356.662121.778
   370.1 2120.48   389.5  2121.6   409.7 2122.49   477.5 2139.96   492.1 2140.08
   505.3 2143.33   531.6 2145.41   544.7 2144.41   570.9 2148.96   587.4 2157.57
   597.3  2165.7   623.5 2175.37   649.8 2182.97   705.6 2191.63   738.4 2202.54
   758.1 2205.72   787.7 2228.94     814 2233.94   869.8 2251.53   894.6 2256.95
#Mann= 4 ,-1 , 0
       0     .12       0  356.66    .045       0   389.5     .12       0
  466.32      .1       0
#XS Ineff= 2 , 0
                          395.49         2128.77
Permanent Ineff=
       F       F
Bank Sta=356.66,389.5
XS Rating Curve= 0 ,0
Exp/Cntr(USF)=0,0
Exp/Cntr=0.3,0.1

Type RM Length L Ch R = 1 ,11904   ,359.9,359.3,375.3
XS GIS Cut Line= 4
1969488.12784456236762.2775789451969369.94588526236590.376547225
1969290.44165809236338.9712883341969183.00351326235986.574173308
#Sta/Elev= 30
       0 2247.54    40.4 2224.58    68.9 2214.54   111.1 2195.71   177.2  2163.1
   211.4  2144.3   225.2 2134.02   241.8 2119.51   252.7 2112.52     263 2110.65
   300.9 2112.48   316.1 2110.93  326.832105.946   362.8 2104.89  388.332105.946
   401.3 2112.21   421.3 2128.98   435.1 2138.47   445.4 2143.78   462.6 2149.14
   503.4 2168.12   545.4 2190.15   603.3 2218.19   644.4 2246.23   668.4 2264.99
   685.6 2276.32   716.5 2285.53   754.2 2307.14   819.4 2334.93   840.7 2346.19
#Mann= 4 ,-1 , 0
       0     .12       0  218.61      .1       0  326.83    .045       0
  388.33      .1       0
#XS Ineff= 2 , 0
          298.14 2130.39
Permanent Ineff=
       F       F
Bank Sta=326.83,388.33
XS Rating Curve= 0 ,0
Exp/Cntr(USF)=0,0
Exp/Cntr=0.3,0.1

Type RM Length L Ch R = 1 ,11545   ,288.7,283.7,278.6
XS GIS Cut Line= 4
 1969711.5991858236775.1701563241969666.47516497236540.955000606
 1969589.1197007236300.2935561971969470.93774139235999.466750687
#Sta/Elev= 30
       0 2241.07    30.5 2224.23    60.6 2216.64   124.1 2195.71   177.6 2171.95
   261.8 2125.03   272.1 2108.74   282.9 2093.88   285.9 2090.14   289.5  2088.8
   299.7  2087.1  308.26  2088.8   320.4 2090.38   327.3 2093.19   337.7 2093.14
   347.9 2098.06   368.6 2096.68   376.8 2098.24   403.5 2110.53   434.3 2118.43
   538.5 2162.89   577.3 2183.83   626.7 2198.36   683.1 2223.67   725.4 2248.41
     750 2265.92   764.1 2278.22   784.5 2298.86   797.7 2308.92   814.5 2318.01
#Mann= 3 ,-1 , 0
       0      .1       0   289.5    .045       0  308.26      .1       0
#XS Ineff= 2 , 0
                          350.49         2112.98
Permanent Ineff=
       F       F
Bank Sta=289.5,308.26
XS Rating Curve= 0 ,0
Exp/Cntr(USF)=0,0
Exp/Cntr=0.3,0.1

Type RM Length L Ch R = 1 ,11261   ,298.7,294.3,288.5
XS GIS Cut Line= 4
1970105.43842335236691.8388449761969952.16589849236432.454572147
1969778.26053376236170.1227507631969636.77820312235960.846803367
#Sta/Elev= 30
       0 2245.46    48.6 2222.46      60  2214.1    71.4 2212.09    94.3  2202.9
     201 2141.85   319.7 2099.82   331.5 2098.81     363  2089.6   374.8 2088.67
   392.4 2090.91   405.5 2081.74  417.532077.895   429.2  2076.7  450.562077.896
   461.4  2081.4   481.1 2082.06   500.2 2093.77   520.5 2111.29   524.4 2117.77
   536.2 2143.27   552.2 2160.55   579.5 2177.41   587.7 2185.08   608.9 2195.98
   666.4 2216.23   713.9  2245.5   776.8 2269.13   833.5 2305.07   868.6 2320.79
#Mann= 3 ,-1 , 0
       0      .1       0  417.53    .045       0  450.56      .1       0
Bank Sta=417.53,450.56
XS Rating Curve= 0 ,0
Exp/Cntr(USF)=0,0
Exp/Cntr=0.3,0.1

Type RM Length L Ch R = 1 ,10967   ,122.7,113.3,103.1
XS GIS Cut Line= 4
1970429.66876438  236494.35309181970246.92075398236285.077144404
1970043.53990369236084.6438426721969781.20808231 235907.79092938
#Sta/Elev= 30
       0 2248.25   112.6 2198.21     120 2196.66   133.1 2188.09   146.1 2185.17
   175.4 2169.27     194 2151.79   203.3 2145.22   245.1 2122.03   300.1 2096.39
   328.1 2086.82   351.5 2081.65   368.2 2070.67   382.1 2069.43   435.3 2070.98
  461.352066.941   472.6 2065.64  486.29 2066.96     509 2067.13   524.4 2082.38
   532.9 2088.65   567.3 2124.08   587.9 2138.13   631.4 2172.78     667 2197.38
   726.1  2228.8   765.9 2247.68   820.7 2266.84   845.1 2283.49   879.8 2301.41
#Mann= 6 ,-1 , 0
       0     .12       0  387.84      .1       0  417.84     .12       0
  461.35    .045       0  486.29     .12       0  527.84      .1       0
#XS Ineff= 2 , 0
          435.18 2073.73  492.52          2073.2
Permanent Ineff=
       F       F
Bank Sta=461.35,486.29
XS Rating Curve= 0 ,0
Exp/Cntr(USF)=0,0
Exp/Cntr=0.3,0.1

Type RM Length L Ch R = 1 ,10854   ,88.4,97.7,105.5
XS GIS Cut Line= 4
1970484.87217568236330.1385480121970226.87109036236073.710640047
1970042.80934047236010.7835460681969816.27180215235870.770761965
#Sta/Elev= 30
       0 2186.85    86.5 2161.87   123.5 2148.39   151.2 2132.32     216 2101.07
   246.4 2092.49   281.6  2085.1   300.2 2078.21   322.4 2067.22   346.1 2063.04
   377.7 2063.97   390.6 2062.38     401 2064.98   426.4 2065.59   444.9  2061.9
   457.6 2061.19   470.7 2061.96   483.7  2063.1   499.2 2082.83   509.6 2098.29
     525 2112.54   596.7 2168.65   634.8  2193.1   670.6 2208.39   700.8  2225.3
   711.1 2227.75   737.3 2239.42   789.8 2257.62   801.7 2260.12   824.6 2276.81
#Mann= 7 ,-1 , 0
       0      .1       0      30     .12       0      60      .1       0
     310     .12       0   444.9    .045       0   470.7     .12       0
  533.76      .1       0
#XS Ineff= 2 , 0
          425.15 2072.65
Permanent Ineff=
       F       F
Bank Sta=444.9,470.7
XS Rating Curve= 0 ,0
Exp/Cntr(USF)=0,0
Exp/Cntr=0.3,0.1

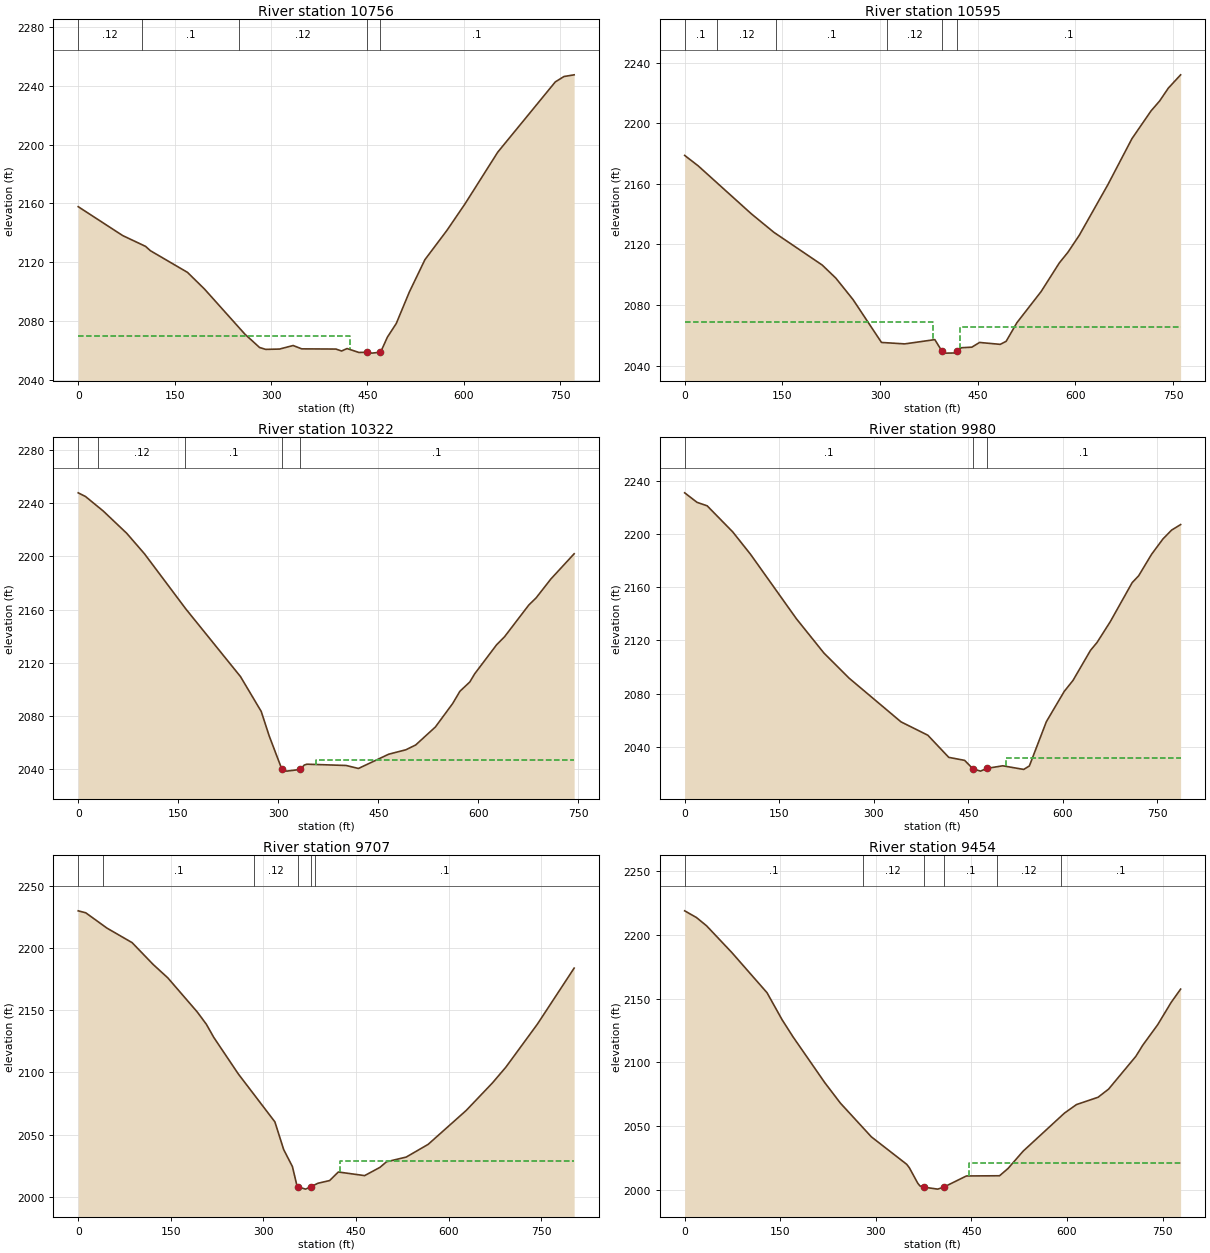
Type RM Length L Ch R = 1 ,10756   ,155.3,161.2,165.9
XS GIS Cut Line= 4
1970543.07973761  236215.29660151970258.33463735236045.393447757
1970099.44372506235900.661131605 1969961.0041183235722.892091114
#Sta/Elev= 30
       0  2157.8    69.2 2138.14   104.9 2130.76   112.3 2127.84   170.1 2113.06
   196.6 2101.68   259.3 2071.05   282.2 2061.94   291.8 2060.64   313.3 2060.86
   334.5 2063.27   347.8    2061   401.1 2060.86   409.9 2059.53   418.4  2061.2
   436.9 2058.54   449.9 2058.67   456.8 2058.09   469.4 2058.65   471.8 2059.91
   481.2    2069     495 2078.29   515.3 2099.67   539.6 2121.75   573.9 2141.72
   602.2 2159.89   652.9 2194.92   742.5 2242.78     756 2246.43   771.8 2247.58
#Mann= 5 ,-1 , 0
       0     .12       0     100      .1       0     250     .12       0
   449.9    .045       0   469.4      .1       0
#XS Ineff= 2 , 0
          422.75 2069.74
Permanent Ineff=
       F       F
Bank Sta=449.9,469.4
XS Rating Curve= 0 ,0
Exp/Cntr(USF)=0,0
Exp/Cntr=0.3,0.1

Type RM Length L Ch R = 1 ,10595   ,279.6,272.5,259.1
XS GIS Cut Line= 4
1970602.04140387236174.0930986671970374.27253684235993.597015361
1970247.49552595235806.6546433651970064.85067975235643.348663231
#Sta/Elev= 30
       0 2178.75    20.8 2171.84   102.2 2140.24     137 2127.96   211.1 2106.38
   232.1 2097.72   258.5 2083.56   302.2 2055.24   337.9 2054.29   384.1 2057.11
  394.912049.551   401.3 2048.19   413.2 2048.28  417.942049.555     425 2051.75
   440.9 2052.12   452.8 2055.24   484.5 2053.98   493.6 2055.98   510.1 2068.26
   547.4 2088.91   575.3 2107.78   588.5 2114.82   606.1 2126.16   650.1 2159.67
   686.8 2189.84   716.1 2208.16   729.3 2214.71   742.6 2223.17   761.5 2231.97
#Mann= 6 ,-1 , 0
       0      .1       0      50     .12       0     140      .1       0
  310.62     .12       0  394.91    .045       0  417.94      .1       0
#XS Ineff= 2 , 0
          381.19 2069.06  422.75         2065.13
Permanent Ineff=
       F       F
Bank Sta=394.91,417.94
XS Rating Curve= 0 ,0
Exp/Cntr(USF)=0,0
Exp/Cntr=0.3,0.1

Type RM Length L Ch R = 1 ,10322   ,336.1,342.4,327
XS GIS Cut Line= 4
1970776.09119849235937.7291800521970619.23150704235795.910828882
1970430.14037215235682.026395368 1970152.9499585235540.208044198
#Sta/Elev= 30
       0 2247.89    10.9 2245.13    37.5 2234.21    72.8 2217.41    99.4 2201.99
   161.3 2160.56   243.3 2109.64   274.4 2083.41   286.3 2065.08  305.462039.776
   312.6 2038.51  333.012039.775   338.9 2043.07   342.9 2043.72   401.7 2042.76
   420.2 2040.51   465.5 2051.23   491.3 2054.57     506 2058.18   535.5  2071.7
   561.4 2089.33   572.3 2098.58   587.1 2105.56   594.4 2111.67   627.2 2133.49
   639.4  2139.7   675.5 2163.42   686.6 2168.87   708.7 2183.06   743.6 2202.04
#Mann= 5 ,-1 , 0
       0      .1       0      30     .12       0     160      .1       0
  305.46    .045       0  333.01      .1       0
#XS Ineff= 2 , 0
                          357.27         2046.53
Permanent Ineff=
       F       F
Bank Sta=305.46,333.01
XS Rating Curve= 0 ,0
Exp/Cntr(USF)=0,0
Exp/Cntr=0.3,0.1

Type RM Length L Ch R = 1 ,9980    ,270.2,272.8,269.5
XS GIS Cut Line= 4
 1970892.1243949235705.662787229 1970584.8513007235484.340208889
1970395.76016581235398.3896930291970206.66903092235331.778043238
#Sta/Elev= 30
       0 2230.98    19.6 2223.83    35.7  2221.2    76.2 2201.61   104.5 2184.73
   177.2  2136.3   220.9 2110.48   260.9 2091.56   343.3 2058.67   385.8 2048.65
     419 2031.99   444.2 2029.73   457.42023.347   469.4 2021.63   479.3 2023.69
   504.7 2025.64   537.9 2022.91   546.9 2025.53   573.9 2058.83   602.2 2081.58
   616.1 2089.83   643.9 2112.47   654.4 2118.48   675.2 2133.98     710  2163.4
   720.3 2168.57   740.8 2184.72   758.8 2196.25   772.6 2202.94   786.9 2207.09
#Mann= 3 ,-1 , 0
       0      .1       0   457.4    .045       0   479.3      .1       0
#XS Ineff= 2 , 0
                          509.31         2031.25
Permanent Ineff=
       F       F
Bank Sta=457.4,479.3
XS Rating Curve= 0 ,0
Exp/Cntr(USF)=0,0
Exp/Cntr=0.3,0.1

Type RM Length L Ch R = 1 ,9707    ,254.2,253.3,252
XS GIS Cut Line= 4
1971001.71130262235419.8773219941970763.19862111235284.505259515
1970501.04954774235177.0671146891970268.98315491235095.414124622
#Sta/Elev= 30
       0 2229.68    12.2  2228.1    46.8 2215.73    87.3 2204.14   121.6 2186.52
   145.1 2175.88   193.1 2148.32   207.7 2138.53   219.7 2127.99   259.5 2098.62
   318.7 2060.16   332.9 2037.95   347.1 2024.24   354.2 2009.41  356.292007.963
   368.4 2006.14  376.67 2007.96   388.2 2010.82   407.4 2013.03   421.5 2019.91
   464.1 2016.99   488.9 2023.61   499.5 2028.09   531.5 2031.89     567 2042.08
   628.8 2069.39   671.1 2091.39   693.1 2104.19   744.1 2138.72   803.6 2183.67
#Mann= 6 ,-1 , 0
       0     .12       0      40      .1       0  284.25     .12       0
  356.29    .045       0  376.67     .12       0  384.25      .1       0
#XS Ineff= 2 , 0
                          424.13         2029.01
Permanent Ineff=
       F       F
Bank Sta=356.29,376.67
XS Rating Curve= 0 ,0
Exp/Cntr(USF)=0,0
Exp/Cntr=0.3,0.1

Type RM Length L Ch R = 1 ,9454    ,235.8,257.5,270.3
XS GIS Cut Line= 4
1971098.40563297235187.8109291721970915.76078676235065.331444071
1970660.05800208234977.2321653151970378.57006264234917.066804213
#Sta/Elev= 30
       0  2218.7    18.6 2213.41    34.4 2206.95    73.9 2186.06   129.2 2154.56
   152.9 2133.34   170.3 2119.75   219.9 2084.03   244.3 2068.06   292.9 2041.62
   348.4 2020.09   352.6 2017.35   365.8  2005.2   369.3  2003.1   374.82002.222
     397 2000.64  406.612002.223   442.1 2010.96   494.1 2011.11   507.5 2016.88
     531 2030.35     596 2060.24   614.8  2066.9   648.6 2072.61   665.1 2078.96
   707.9 2104.65   718.8 2113.41   742.3 2129.52   763.3 2146.91   778.2 2157.36
#Mann= 6 ,-1 , 0
       0      .1       0  279.91     .12       0   374.8    .045       0
  406.61      .1       0  489.91     .12       0  590.36      .1       0
#XS Ineff= 2 , 0
                          445.79         2021.18
Permanent Ineff=
       F       F
Bank Sta=374.8,406.61
XS Rating Curve= 0 ,0
Exp/Cntr(USF)=0,0
Exp/Cntr=0.3,0.1