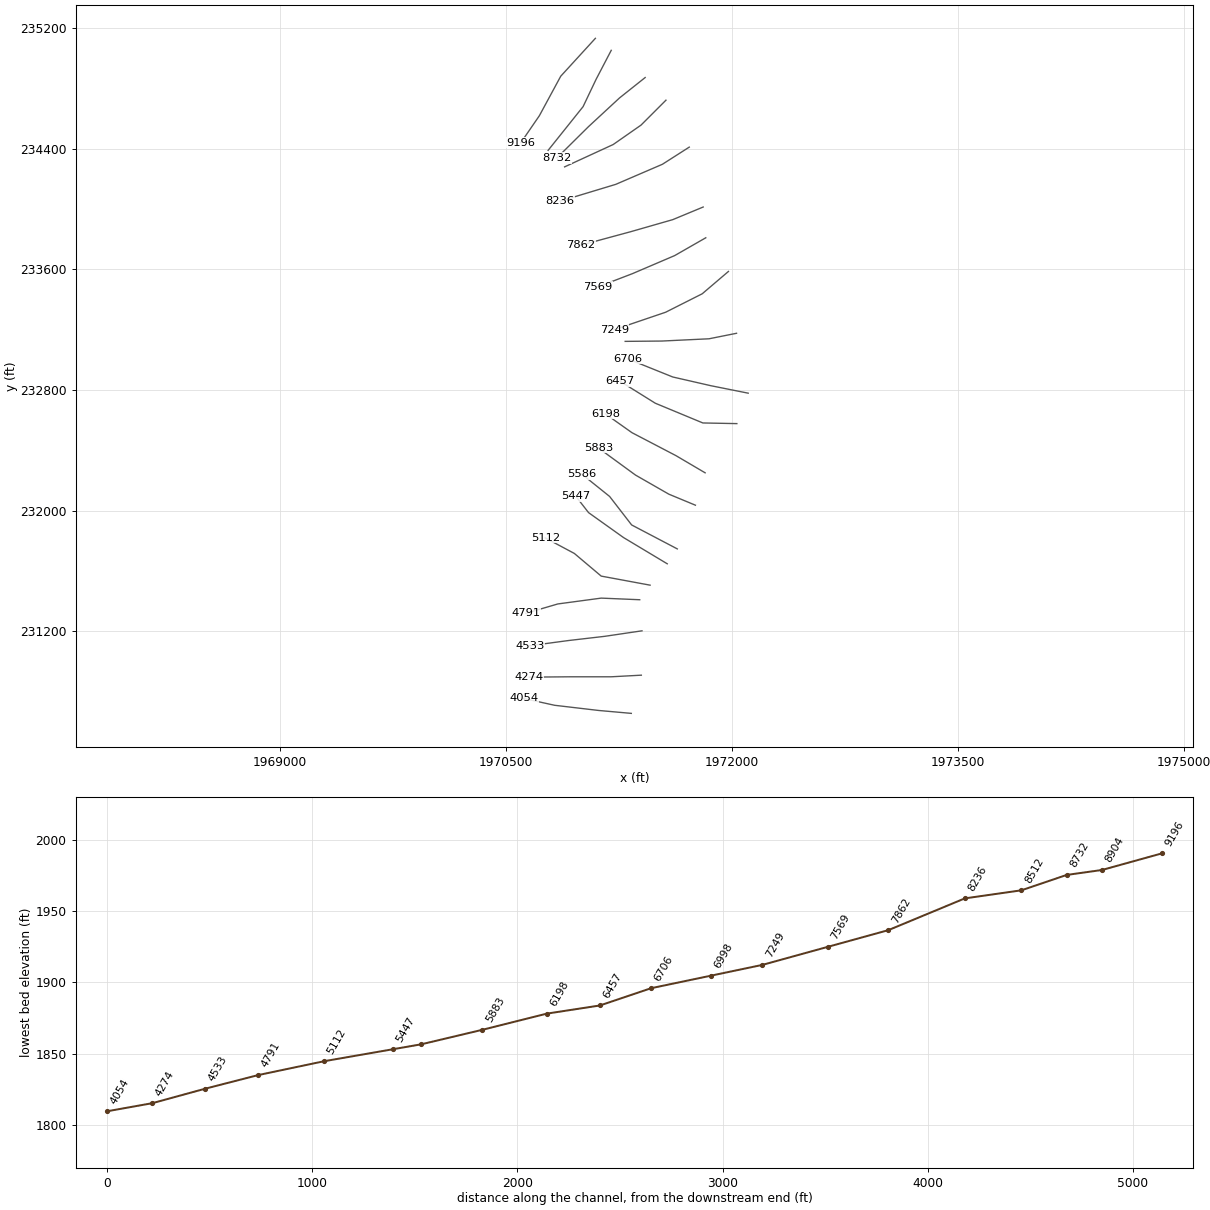
HEC-RAS study PRKRCK.prj: PRKRCK

--- PRKRCK.g01 (geometry) --- (continued)

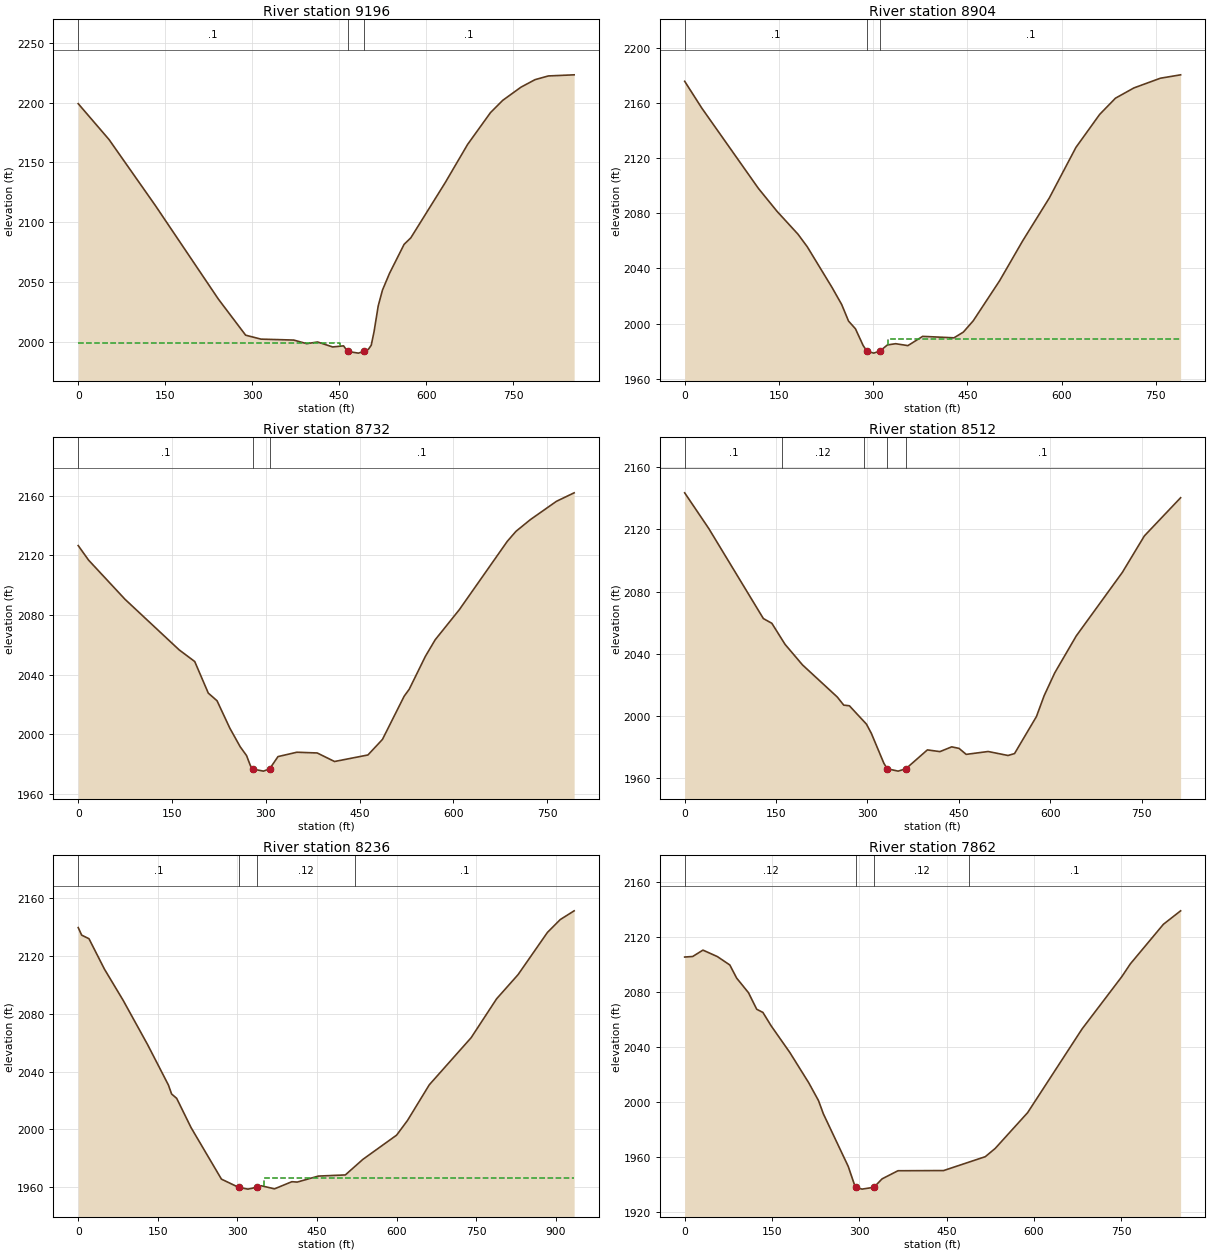
Type RM Length L Ch R = 1 ,9196    ,282.7,291.9,288.1
XS GIS Cut Line= 4
1971091.95934428235134.0918567591970862.04171435234882.686597869
1970720.22336318234620.5375244951970597.74387808234442.190204085
#Sta/Elev= 30
       0 2199.27    53.1 2169.25   133.1 2113.88   241.8 2035.45   288.7 2005.31
   315.1 2002.01   371.7 2001.22   393.9  1998.2   412.7 1999.59   438.8 1995.45
   457.5 1996.38  464.631991.672   483.2 1990.28  491.921991.674   500.4 1993.54
   505.2 1996.84   510.1 2008.28   517.3  2029.9   524.6 2043.09   536.7 2057.06
   561.9 2081.41   573.5 2086.89   632.8 2133.12   671.4 2165.13   710.8 2191.76
   731.9 2202.04   763.4  2213.1   787.6 2219.38   810.6  2222.5   855.1 2223.44
#Mann= 3 ,-1 , 0
       0      .1       0  464.63    .045       0  491.92      .1       0
#XS Ineff= 2 , 0
          451.12  1998.8
Permanent Ineff=
       F       F
Bank Sta=464.63,491.92
XS Rating Curve= 0 ,0
Exp/Cntr(USF)=0,0
Exp/Cntr=0.3,0.1

Type RM Length L Ch R = 1 ,8904    ,180,171.9,163.8
XS GIS Cut Line= 4
 1971197.2487262235054.5876295891971096.25687007234861.198968903
1971010.30635421234680.7028855971970778.23996139234390.619894569
#Sta/Elev= 30
       0 2175.66    27.2 2156.28   117.4 2098.03   147.2 2081.34   180.3  2064.9
   195.1  2055.8     235 2025.95     250 2013.88   260.9 2001.87   271.9  1996.3
   284.2 1984.14  289.971980.214   300.9 1978.66  311.071980.213   322.7 1984.59
   335.9 1985.49   355.4 1984.11   378.9 1990.81   428.8 1989.75   443.6 1993.87
   459.4 2002.07   501.4 2031.11   538.1    2060   580.6 2091.14   622.9 2127.73
   660.7 2151.66   685.9 2163.43   715.3 2170.87   757.3 2177.88   789.6 2180.35
#Mann= 3 ,-1 , 0
       0      .1       0  289.97    .045       0  311.07      .1       0
#XS Ineff= 2 , 0
                          323.27          1988.7
Permanent Ineff=
       F       F
Bank Sta=289.97,311.07
XS Rating Curve= 0 ,0
Exp/Cntr(USF)=0,0
Exp/Cntr=0.3,0.1

Type RM Length L Ch R = 1 ,8732    ,224.1,220.7,218.2
XS GIS Cut Line= 4
1971422.41928052234873.9440492551971252.23725911234738.571986775
1971045.31139218234547.1172126961970836.45163864234340.191345762
#Sta/Elev= 30
       0 2126.44    16.6 2116.69      75 2090.38   161.5 2056.52   186.4 2048.71
   208.1 2027.52   222.1 2022.39   242.5 2004.08   259.2  1991.5   269.3 1985.65
   275.5 1978.85   280.1  1976.5   296.4 1975.21   306.3 1976.75   319.6 1984.95
   349.8 1987.88   382.3 1987.39   410.1 1981.66   463.5 1986.04   486.7 1996.46
   521.5 2025.48   529.5 2030.08   555.4 2052.18   571.1  2063.3   609.7 2083.46
   686.5 2129.34   700.4 2136.03   723.5  2143.9   765.1 2156.14   793.4 2161.82
#Mann= 3 ,-1 , 0
       0      .1       0   280.1    .045       0   306.3      .1       0
Bank Sta=280.1,306.3
XS Rating Curve= 0 ,0
Exp/Cntr(USF)=0,0
Exp/Cntr=0.3,0.1

Type RM Length L Ch R = 1 ,8512    ,281.2,276.2,270.7
XS GIS Cut Line= 4
1971560.38965571234723.6781435271971394.93491268234558.223400497
1971210.14130358234429.2976267061970887.82686911234281.032986848
#Sta/Elev= 30
       0 2143.56    39.6 2120.56   129.2 2062.62   143.1 2059.59   164.8 2046.02
   193.4 2032.81   250.4 2012.18   261.1 2006.92   270.4  2006.5   298.4 1994.68
   306.4 1988.78   327.1  1969.4   332.61965.956   350.4 1964.44  363.091965.956
   398.4  1978.1     419    1977   438.4 1980.07   450.4 1979.07   462.1 1975.22
   498.2 1977.07   530.8  1974.5   541.5 1975.75   577.4 1999.55   590.1 2013.02
   607.4 2027.64   642.7 2051.41   718.5 2092.39   754.6 2115.83   814.1 2140.41
#Mann= 5 ,-1 , 0
       0      .1       0     160     .12       0  293.99      .1       0
   332.6    .045       0  363.09      .1       0
Bank Sta=332.6,363.09
XS Rating Curve= 0 ,0
Exp/Cntr(USF)=0,0
Exp/Cntr=0.3,0.1

Type RM Length L Ch R = 1 ,8236    ,376.1,373.3,368.4
XS GIS Cut Line= 4
1971715.10058426234412.1075235341971536.75326385 234298.22309002
1971227.33140676234164.9997904361970857.74418856234053.264119818
#Sta/Elev= 30
       0 2139.61     6.5  2134.4    20.3  2131.9    49.4  2110.9    84.5 2089.43
   131.1 2058.45     170 2030.74     176 2024.56   185.6 2021.52   212.8 2001.22
   269.9 1965.68  302.521959.966   319.9 1958.77   337.8 1960.16   344.9  1961.1
   369.9 1958.96   402.6  1963.9   412.8 1963.65   452.5 1967.79   503.4 1968.58
   536.5 1979.35     600 1996.09   620.5 2006.22   661.6 2030.89   740.5 2063.48
   788.4 2090.33     829 2107.12   884.2 2136.24   908.4 2145.15   934.6 2151.19
#Mann= 4 ,-1 , 0
       0      .1       0  302.52    .045       0   337.8     .12       0
  521.61      .1       0
#XS Ineff= 2 , 0
                           350.3         1966.18
Permanent Ineff=
       F       F
Bank Sta=302.52,337.8
XS Rating Curve= 0 ,0
Exp/Cntr(USF)=0,0
Exp/Cntr=0.3,0.1

Type RM Length L Ch R = 1 ,7862    ,283.5,293.2,289.4
XS GIS Cut Line= 4
1971807.49738881234014.5863876811971605.51367654233930.784634718
1971328.32326289233851.2804075471970995.26501393233761.032365894
#Sta/Elev= 30
       0 2105.37    13.7 2105.76    31.4  2110.4    56.3 2105.67    77.6 2099.58
    89.3 2090.03   109.6 2079.45   123.8 2067.36   134.4 2065.07   148.6  2055.3
   180.6 2035.97   213.3 2013.78   229.9 2000.94   238.3 1991.29   281.1 1952.95
   291.3 1940.23  294.581937.842   304.7 1936.51   325.11937.843   339.2 1943.98
   366.4 1949.88   444.9 1950.02   516.5 1960.12   533.5 1966.11   589.2 1992.13
   682.8 2053.06   751.1 2091.13   765.7 2100.38   822.5 2129.19   852.1 2138.99
#Mann= 4 ,-1 , 0
       0     .12       0  294.58    .045       0   325.1     .12       0
  488.68      .1       0
Bank Sta=294.58,325.1
XS Rating Curve= 0 ,0
Exp/Cntr(USF)=0,0
Exp/Cntr=0.3,0.1

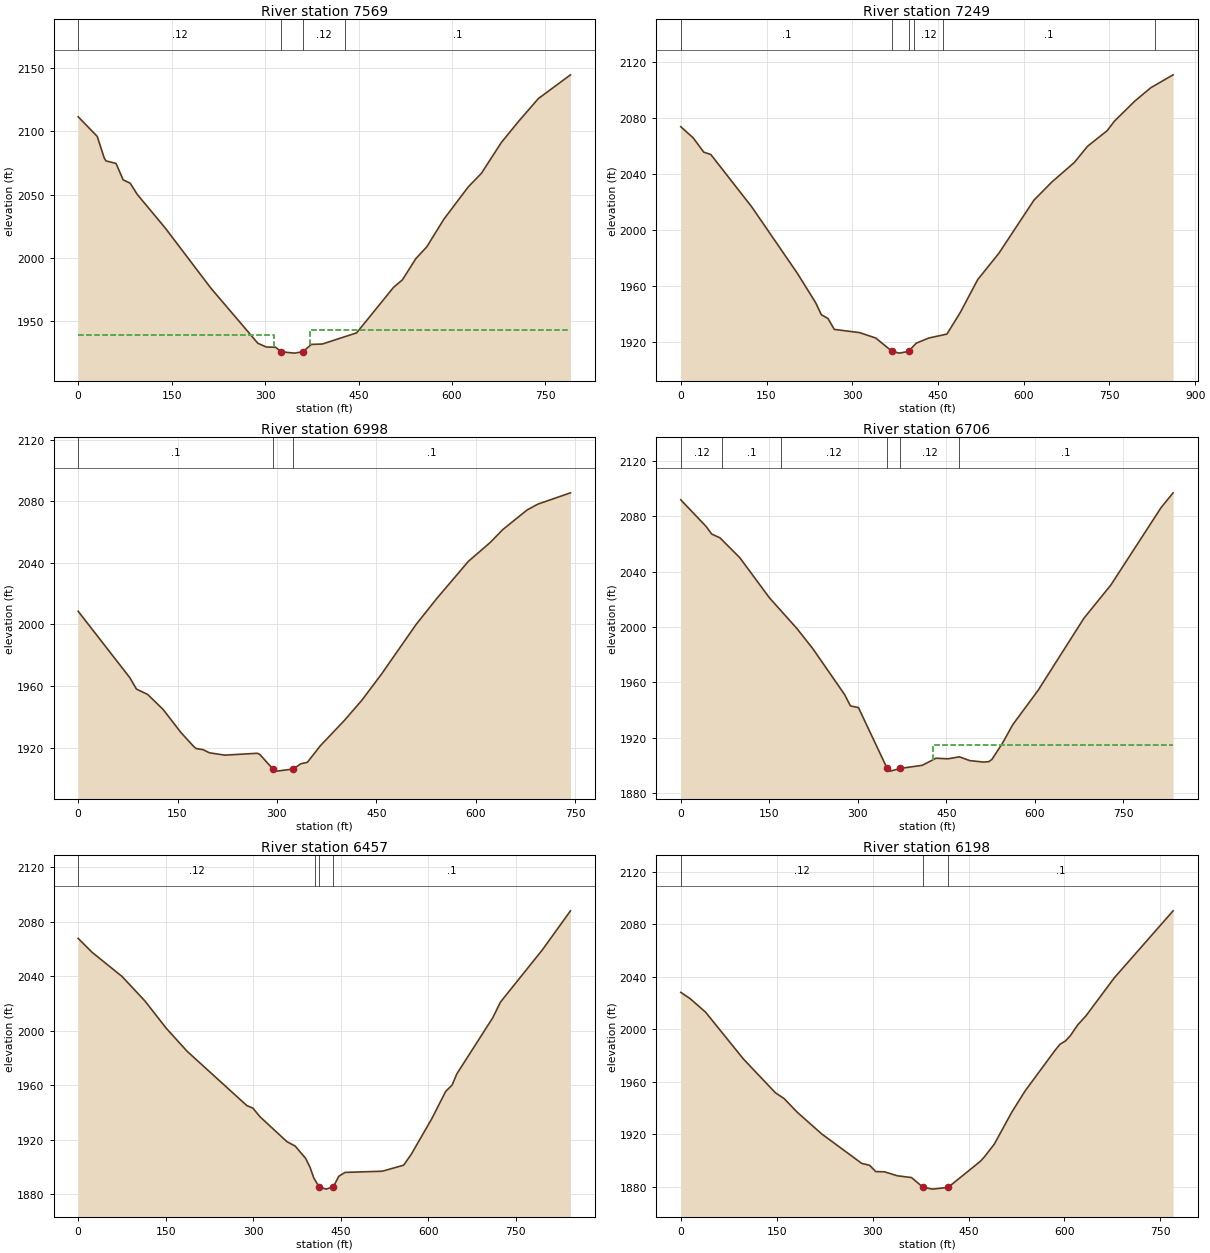
Type RM Length L Ch R = 1 ,7569    ,316.9,320.4,321.8
XS GIS Cut Line= 4
1971824.68749198233810.4539125131971618.40625392233692.271953206
1971336.91831448233571.9412310021971107.00068455233483.841952245
#Sta/Elev= 30
       0 2111.46    30.6 2095.94    41.9 2078.83    44.7  2076.6    60.8 2074.62
    72.2 2061.63    83.5 2059.02    94.8 2050.21   140.2 2023.37   212.9 1976.25
   288.4 1932.68   301.9 1929.72     317 1929.54  325.46 1926.01   346.9  1924.9
  360.791926.009   374.1 1931.77   391.9 1932.09   446.9  1940.9   506.1  1976.8
   520.4 1982.75   541.9 1999.47   559.4 2008.75   587.2  2030.8   626.1 2056.13
   647.2 2066.84     679 2091.04   706.9 2107.87   738.5 2125.77   790.1 2144.54
#Mann= 4 ,-1 , 0
       0     .12       0  325.46    .045       0  360.79     .12       0
  427.74      .1       0
#XS Ineff= 2 , 0
          313.75 1939.13  372.67         1943.28
Permanent Ineff=
       F       F
Bank Sta=325.46,360.79
XS Rating Curve= 0 ,0
Exp/Cntr(USF)=0,0
Exp/Cntr=0.3,0.1

Type RM Length L Ch R = 1 ,7249    ,259.8,250.9,239.7
XS GIS Cut Line= 4
1971975.10089474233586.9825712771971801.05110012233438.717931418
1971558.24089282233316.2384463181971216.58759227233200.205249907
#Sta/Elev= 30
       0 2073.86    21.7 2065.93    40.3 2055.71    52.5 2054.07   124.1 2016.67
   204.3 1969.02   236.1 1948.16   245.9 1939.65   257.6 1936.92   268.6 1929.15
   312.7 1926.88   341.2 1922.98  369.741913.459   382.5 1912.21  398.611913.458
   411.9 1919.32     434    1923   465.7 1925.81   489.1 1941.28   519.5 1964.68
   556.8 1983.64   617.9 2021.43   649.1 2034.33   688.7 2048.38   711.5 2059.84
   746.1 2071.08   758.5 2077.75   794.7 2092.29   822.4 2101.73   861.4 2110.93
#Mann= 6 ,-1 , 0
       0      .1       0  369.74    .045       0  398.61      .1       0
  408.64     .12       0  458.64      .1       0  830.59    .035       0
Bank Sta=369.74,398.61
XS Rating Curve= 0 ,0
Exp/Cntr(USF)=0,0
Exp/Cntr=0.3,0.1

Type RM Length L Ch R = 1 ,6998    ,295.9,292,284.7
XS GIS Cut Line= 4
1972028.81996715233176.5688580451971846.17512095233140.039888804
1971532.45573806233124.9985485291971289.64553075233122.849785632
#Sta/Elev= 30
       0 2008.57      78  1965.4      88 1957.98   104.8 1954.53   128.2 1944.78
   154.9 1929.88   174.5 1920.62   178.3 1919.31   188.7 1918.58   198.2 1916.56
   221.2 1915.04   270.5 1916.25   274.2 1915.52  293.941906.048     300 1904.65
  324.791906.046   336.1 1909.44     346 1910.38   365.7 1921.19   401.9  1937.6
   428.1 1950.64   457.7 1967.59   510.2 2000.01   541.2 2016.78     589 2040.98
   621.8 2053.18   640.8 2061.58   677.5 2074.35   693.8 2078.18   743.2 2085.55
#Mann= 3 ,-1 , 0
       0      .1       0  293.94    .045       0  324.79      .1       0
Bank Sta=293.94,324.79
XS Rating Curve= 0 ,0
Exp/Cntr(USF)=0,0
Exp/Cntr=0.3,0.1

Type RM Length L Ch R = 1 ,6706    ,247.8,249.2,242.1
XS GIS Cut Line= 4
1972106.17543142232779.0477221921971859.06769833232828.469268812
1971605.51367654232886.4858670171971306.83563393233006.816589221
#Sta/Elev= 30
       0 2091.93    43.1  2072.6    52.3 2067.22    66.5 2064.42     100 2050.09
   150.2 2021.12   196.6 1999.01   223.8 1984.31   277.5 1951.24   287.5 1942.99
     301 1941.79  349.671897.831   351.5 1896.17   354.9 1895.87  372.031897.828
   409.2 1900.08   432.3  1905.2   452.5 1904.76   472.1  1906.2   489.5 1903.49
   513.1  1902.4     522 1902.74   527.2 1904.37   544.9 1915.96   562.6 1929.55
   605.1 1954.06   682.9 2006.27   728.9 2030.52   813.7 2086.27   834.1 2096.97
#Mann= 6 ,-1 , 0
       0     .12       0      70      .1       0     170     .12       0
  349.67    .045       0  372.03     .12       0     472      .1       0
#XS Ineff= 2 , 0
                          427.68         1914.92
Permanent Ineff=
       F       F
Bank Sta=349.67,372.03
XS Rating Curve= 0 ,0
Exp/Cntr(USF)=0,0
Exp/Cntr=0.3,0.1

Type RM Length L Ch R = 1 ,6457    ,261.5,258.8,259.6
XS GIS Cut Line= 4
1972030.96873005232577.0640099211971805.34862591232581.361535714
1971489.48048013  232712.43607241971255.26532441232858.551949363
#Sta/Elev= 30
       0 2067.75    23.8 2057.57    75.3 2039.78   114.7 2021.71   150.8 2001.89
   186.9 1984.85   289.2 1945.04   299.3 1943.29   311.8 1936.81   357.8 1918.61
     372 1915.36   389.7 1906.41   397.2    1900   403.9 1891.88  412.861885.553
   424.8 1883.79  437.451885.554   446.6 1893.22   457.4 1896.05   521.2 1896.93
   557.8 1901.36   571.2 1909.61     606 1935.43   629.8 1955.48   640.8 1960.14
   648.8 1968.25   710.4 2009.46   723.7 2021.01   795.5 2059.33   843.7 2087.97
#Mann= 4 ,-1 , 0
       0     .12       0  405.66      .1       0  412.86    .045       0
  437.45      .1       0
Bank Sta=412.86,437.45
XS Rating Curve= 0 ,0
Exp/Cntr(USF)=0,0
Exp/Cntr=0.3,0.1

Type RM Length L Ch R = 1 ,6198    ,311.2,314.9,311.5
XS GIS Cut Line= 4
1971820.38996619232250.452049652 1971627.0013055232364.336483167
1971334.76955158232516.8986488191971158.57099407232641.526896816
#Sta/Elev= 30
       0 2028.08    14.4  2023.4    38.8 2012.97    98.1  1977.2     148 1951.53
   161.6 1947.12   181.9  1936.8   220.2 1920.24     283 1897.69   295.2 1896.28
   304.9 1891.45   318.6 1891.29   338.5 1888.26   360.9 1886.89  378.861879.463
     394 1878.08  418.161879.463   468.1 1899.13   474.6 1902.54   490.3 1912.37
   517.1  1936.3   538.4 1952.89   585.3 1983.89   593.3 1988.65   601.3 1990.92
   609.4 1995.15     621 2003.45   633.5 2010.08   677.8 2039.08   769.9 2090.23
#Mann= 3 ,-1 , 0
       0     .12       0  378.86    .045       0  418.16      .1       0
Bank Sta=378.86,418.16
XS Rating Curve= 0 ,0
Exp/Cntr(USF)=0,0
Exp/Cntr=0.3,0.1

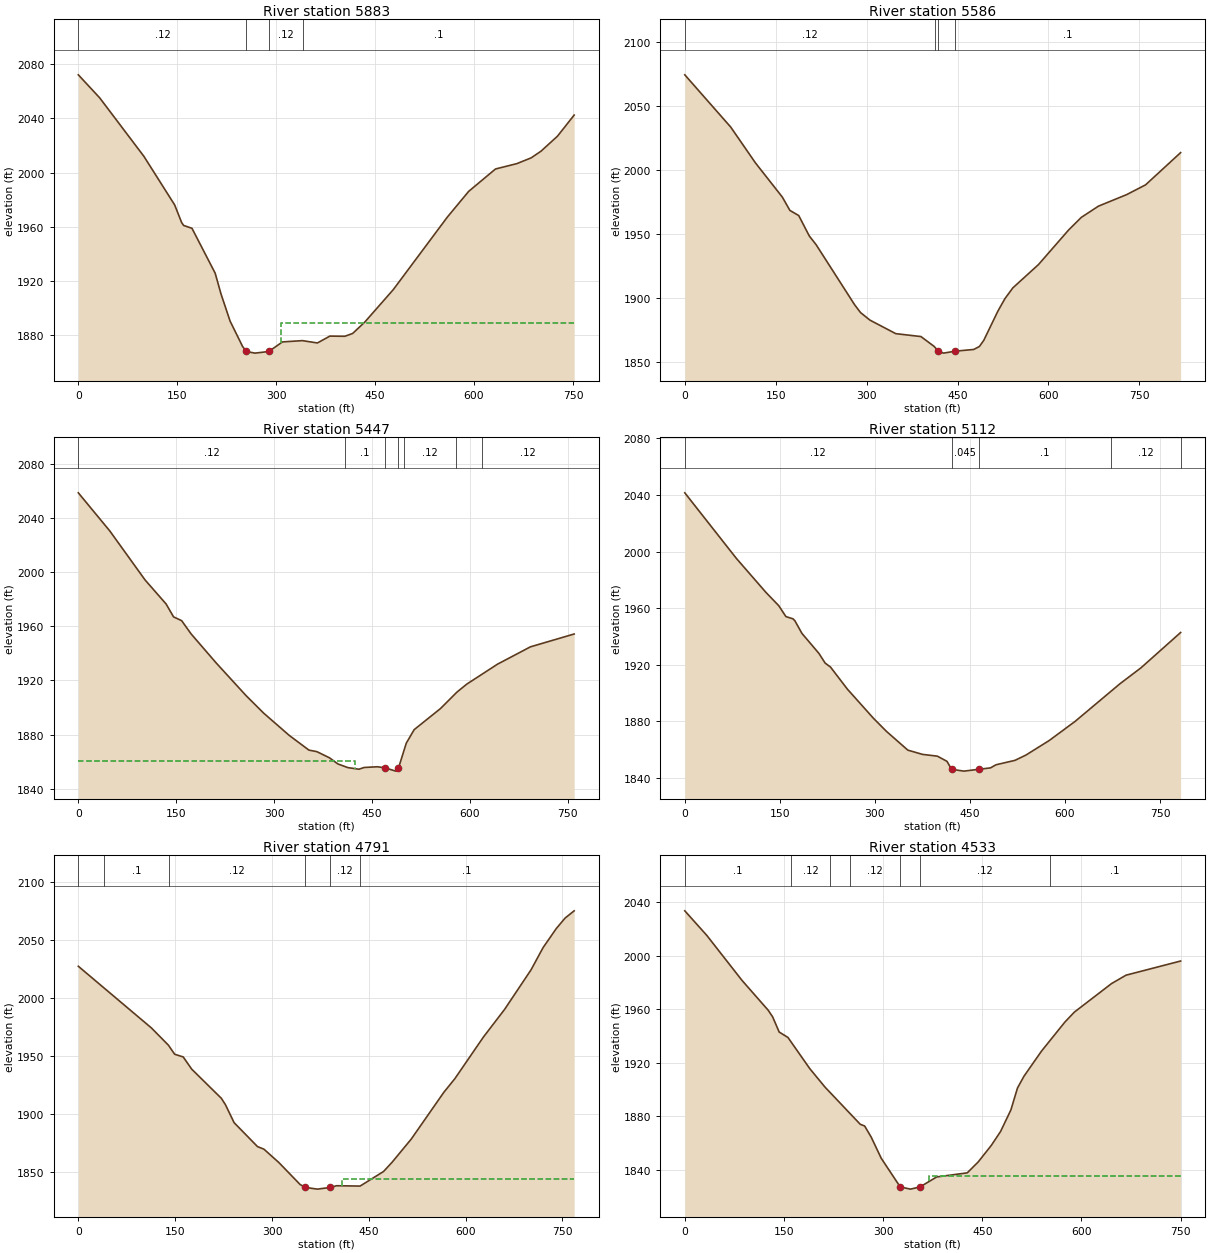
Type RM Length L Ch R = 1 ,5883    ,303.9,297.1,283.1
XS GIS Cut Line= 4
 1971755.9270793232035.5757600021971579.72852178232108.633698483
1971358.40594344232235.4107093771971111.29821034232415.906792683
#Sta/Elev= 30
       0 2072.07    32.4 2055.08    99.5 2011.88   146.1 1976.06   156.7 1963.04
   159.7 1960.94   172.3 1958.85   207.5 1925.71   216.3 1910.44   230.1 1890.39
     249 1871.71  254.871867.946   267.9 1866.74  288.771867.946   309.5 1875.01
   339.8 1875.96   362.5 1874.24   381.4  1879.3   404.1 1879.17   415.9 1881.24
   434.3 1889.62   477.6 1913.63   559.4 1967.03   591.9  1986.1   632.5 2002.59
     665 2006.56   686.6 2010.81   701.6 2015.75   726.5  2026.8   751.8 2042.37
#Mann= 4 ,-1 , 0
       0     .12       0  254.87    .045       0  288.77     .12       0
  340.74      .1       0
#XS Ineff= 2 , 0
                          306.65         1889.13
Permanent Ineff=
       F       F
Bank Sta=254.87,288.77
XS Rating Curve= 0 ,0
Exp/Cntr(USF)=0,0
Exp/Cntr=0.3,0.1

Type RM Length L Ch R = 1 ,5586    ,132.9,138.6,143.5
XS GIS Cut Line= 4
1971635.59635709231745.4927689741971332.62078868231904.501223315
1971186.50491172232093.5923582081971001.71130262232241.856998066
#Sta/Elev= 30
       0 2074.28    75.8  2033.4   116.5 2005.45     161 1978.61   173.4 1968.23
     188 1964.21   205.4 1948.26   216.6 1941.49   280.3 1894.38     290 1888.32
   305.5 1882.42   348.1 1871.84   389.6 1869.57   411.3 1861.92  418.461858.155
   426.9 1856.61  446.231858.151   476.7 1859.47   486.1 1861.81   493.3 1866.61
   516.5 1889.36   528.2 1899.22   541.2 1907.61   583.5 1925.84   633.3 1952.92
   654.3  1962.8   682.4 1971.54     729 1980.57   760.2  1988.2   818.1 2013.43
#Mann= 4 ,-1 , 0
       0     .12       0  412.17      .1       0  418.46    .045       0
  446.23      .1       0
Bank Sta=418.46,446.23
XS Rating Curve= 0 ,0
Exp/Cntr(USF)=0,0
Exp/Cntr=0.3,0.1

Type RM Length L Ch R = 1 ,5447    ,337.1,335.2,326.8
XS GIS Cut Line= 4
 1971568.9847073231646.6496757351971278.90171627231820.699470352
1971046.83532345231986.1542133821970963.03357049232093.592358208
#Sta/Elev= 30
       0 2058.38    48.3 2030.22   102.2 1994.15   134.5 1976.39   145.9 1966.89
   158.3  1964.1   172.7 1954.39     211 1933.02   256.9 1908.87   283.7 1896.01
   323.3 1879.41   353.3 1868.64   365.4 1867.51   384.7 1862.98   397.6 1858.45
   412.9 1855.74   429.9 1854.54   437.9 1855.83   458.1 1856.36   470.2 1855.53
   486.3 1853.14  490.381855.276   502.4 1873.74   514.5 1883.72   554.8 1899.28
   579.9 1911.35   595.1 1917.31   642.2 1932.02   692.6  1944.8   759.6 1954.27
#Mann= 7 ,-1 , 0
       0     .12       0  408.29      .1       0   470.2    .045       0
  490.38      .1       0  498.29     .12       0  578.29      .1       0
  618.29     .12       0
#XS Ineff= 2 , 0
          423.75 1860.25
Permanent Ineff=
       F       F
Bank Sta=470.2,490.38
XS Rating Curve= 0 ,0
Exp/Cntr(USF)=0,0
Exp/Cntr=0.3,0.1

Type RM Length L Ch R = 1 ,5112    ,286.1,321.3,342.9
XS GIS Cut Line= 4
1971455.10027378231504.8313245661971130.63707641231564.996685668
  1970952.289756231715.4100884231970758.90109532231818.550707455
#Sta/Elev= 30
       0 2041.55    81.5 1995.13   128.2 1971.08   148.3 1961.74   159.6 1954.03
   170.8 1952.44   173.7 1951.13   184.9 1942.14   211.7    1928   221.5 1921.16
     230 1918.33   256.6 1902.74   298.4  1881.8   318.4 1872.82     352  1859.6
   375.3 1856.59   398.6 1855.35   413.8 1851.67  420.961846.045   440.5 1844.76
  464.131846.047   482.5 1847.06   491.1 1849.25   521.1 1852.38   538.3  1856.1
   575.1  1866.4     616 1879.94   686.7 1906.52   720.1 1917.87   782.5 1942.78
#Mann= 5 ,-1 , 0
       0     .12       0  420.96    .045       0  464.13      .1       0
   673.3     .12       0  782.47      .1       0
Bank Sta=420.96,464.13
XS Rating Curve= 0 ,0
Exp/Cntr(USF)=0,0
Exp/Cntr=0.3,0.1

Type RM Length L Ch R = 1 ,4791    ,256.7,257.7,256.9
XS GIS Cut Line= 4
 1971386.3398611231408.1369942231971130.63707641231418.880808706
1970842.70284828231380.2030765681970629.97532153 231317.88895257
#Sta/Elev= 30
       0 2027.39   113.2 1974.17   139.5 1959.32   149.3 1951.45   162.5 1949.14
   175.6 1938.62   221.6 1913.42   228.1 1907.73   241.3 1892.42   277.6 1871.75
   287.5 1869.55   310.7 1857.98   343.7 1838.98  351.911836.525   370.3 1835.06
  390.541836.525     400 1837.98   436.5  1837.7   472.9  1850.3   486.1 1858.29
   515.7 1878.23   566.3 1918.68   583.3 1930.39   627.7 1966.44   660.3 1990.14
   701.3 2024.31     720 2043.52   740.5 2060.01   754.2 2069.06   768.1 2075.24
#Mann= 6 ,-1 , 0
       0     .12       0      40      .1       0     140     .12       0
  351.91    .045       0  390.54     .12       0  435.93      .1       0
#XS Ineff= 2 , 0
                          407.95         1843.88
Permanent Ineff=
       F       F
Bank Sta=351.91,390.54
XS Rating Curve= 0 ,0
Exp/Cntr(USF)=0,0
Exp/Cntr=0.3,0.1

Type RM Length L Ch R = 1 ,4533    ,262.2,259.2,256.8
XS GIS Cut Line= 4
1971401.38120137231201.8557561591971154.27346827231165.326786918
1970913.61202387231137.3928692641970657.90923918 231103.01266292
#Sta/Elev= 30
       0 2033.69    33.4 2015.25    86.4 1981.75   126.2 1959.33   132.9 1954.38
   142.8 1943.03   156.1 1938.96   189.2  1915.6   212.2  1901.8   265.4 1874.06
   272.1 1872.75     282 1864.46   297.1  1848.7  325.951827.173   341.4 1825.55
  355.751827.172     381 1834.65   427.3 1837.72   443.8 1845.84   463.6  1858.2
   477.7 1868.65   493.3 1884.75   503.3 1901.18   513.2 1910.05   539.7 1928.81
   574.8 1950.37   589.3 1957.92   645.6 1979.29   667.5 1985.56   750.1 1996.15
#Mann= 7 ,-1 , 0
       0      .1       0     160     .12       0     220      .1       0
  249.79     .12       0  325.95    .045       0  355.75     .12       0
  552.07      .1       0
#XS Ineff= 2 , 0
                          369.95         1835.67
Permanent Ineff=
       F       F
Bank Sta=325.95,355.75
XS Rating Curve= 0 ,0
Exp/Cntr(USF)=0,0
Exp/Cntr=0.3,0.1

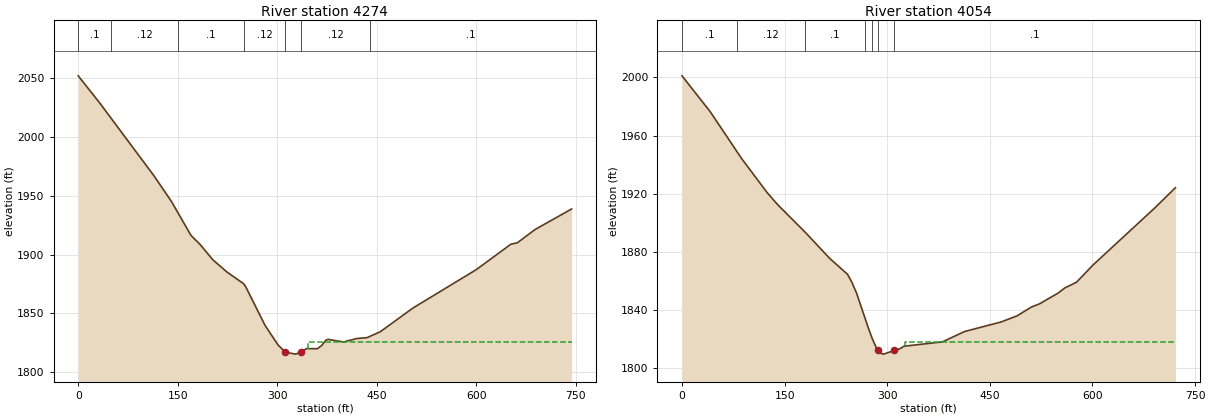
Type RM Length L Ch R = 1 ,4274    ,222.8,219.5,217.9
XS GIS Cut Line= 4
1971397.08367558230907.475239338 1971197.2487262230896.731424855
1970932.95088993230896.7314248551970653.61171339230894.582661959
#Sta/Elev= 30
       0 2051.95      32  2029.2   114.2 1966.98   140.5 1945.19     170 1916.32
   183.2 1908.93   202.9 1895.62   223.8 1885.36   248.8 1875.45   252.1 1873.15
   281.6 1839.88   301.3 1823.14  312.181817.069   327.5 1815.36  335.891817.071
     344 1820.05   360.4 1819.96   366.9 1822.59   373.5  1827.3   376.8 1827.93
   399.7 1825.69   419.4 1828.53   435.8 1829.44   455.5 1834.45   504.7 1854.58
   599.9 1887.11   652.2 1908.77   662.2 1910.06   688.4 1921.19   743.8 1938.76
#Mann= 7 ,-1 , 0
       0      .1       0      50     .12       0     150      .1       0
  250.12     .12       0  312.18    .045       0  335.89     .12       0
  440.12      .1       0
#XS Ineff= 2 , 0
                          346.86         1825.52
Permanent Ineff=
       F       F
Bank Sta=312.18,335.89
XS Rating Curve= 0 ,0
Exp/Cntr(USF)=0,0
Exp/Cntr=0.3,0.1

Type RM Length L Ch R = 1 ,4054    ,212.9,225.3,224.9
XS GIS Cut Line= 4
1971330.47202579 230653.921217551971113.44697324230673.260083619
1970821.21521932230707.6402899631970617.08274415 230752.76431079
#Sta/Elev= 30
       0 2001.06      41 1976.56    87.1 1944.23   124.2 1920.91   139.8 1912.51
   180.2 1893.47   215.6 1875.68     242 1864.59   248.6 1858.85   255.2 1851.61
   272.4 1827.67   278.3 1820.16  285.771812.261   288.9  1810.5   294.8 1809.72
  310.331812.259     318 1813.29   324.6 1815.17   380.7 1818.14     413 1825.26
   466.6 1831.85   489.9 1836.06   510.6 1842.05     523 1844.39   549.8 1851.72
   559.9 1855.32   576.7 1859.16   600.2 1870.74     691  1910.2   721.2 1924.11
#Mann= 7 ,-1 , 0
       0      .1       0      80     .12       0     180      .1       0
  267.88     .12       0  277.88      .1       0  285.77    .045       0
  310.33      .1       0
#XS Ineff= 2 , 0
                           325.3         1818.39
Permanent Ineff=
       F       F
Bank Sta=285.77,310.33
XS Rating Curve= 0 ,0
Exp/Cntr(USF)=0,0
Exp/Cntr=0.3,0.1