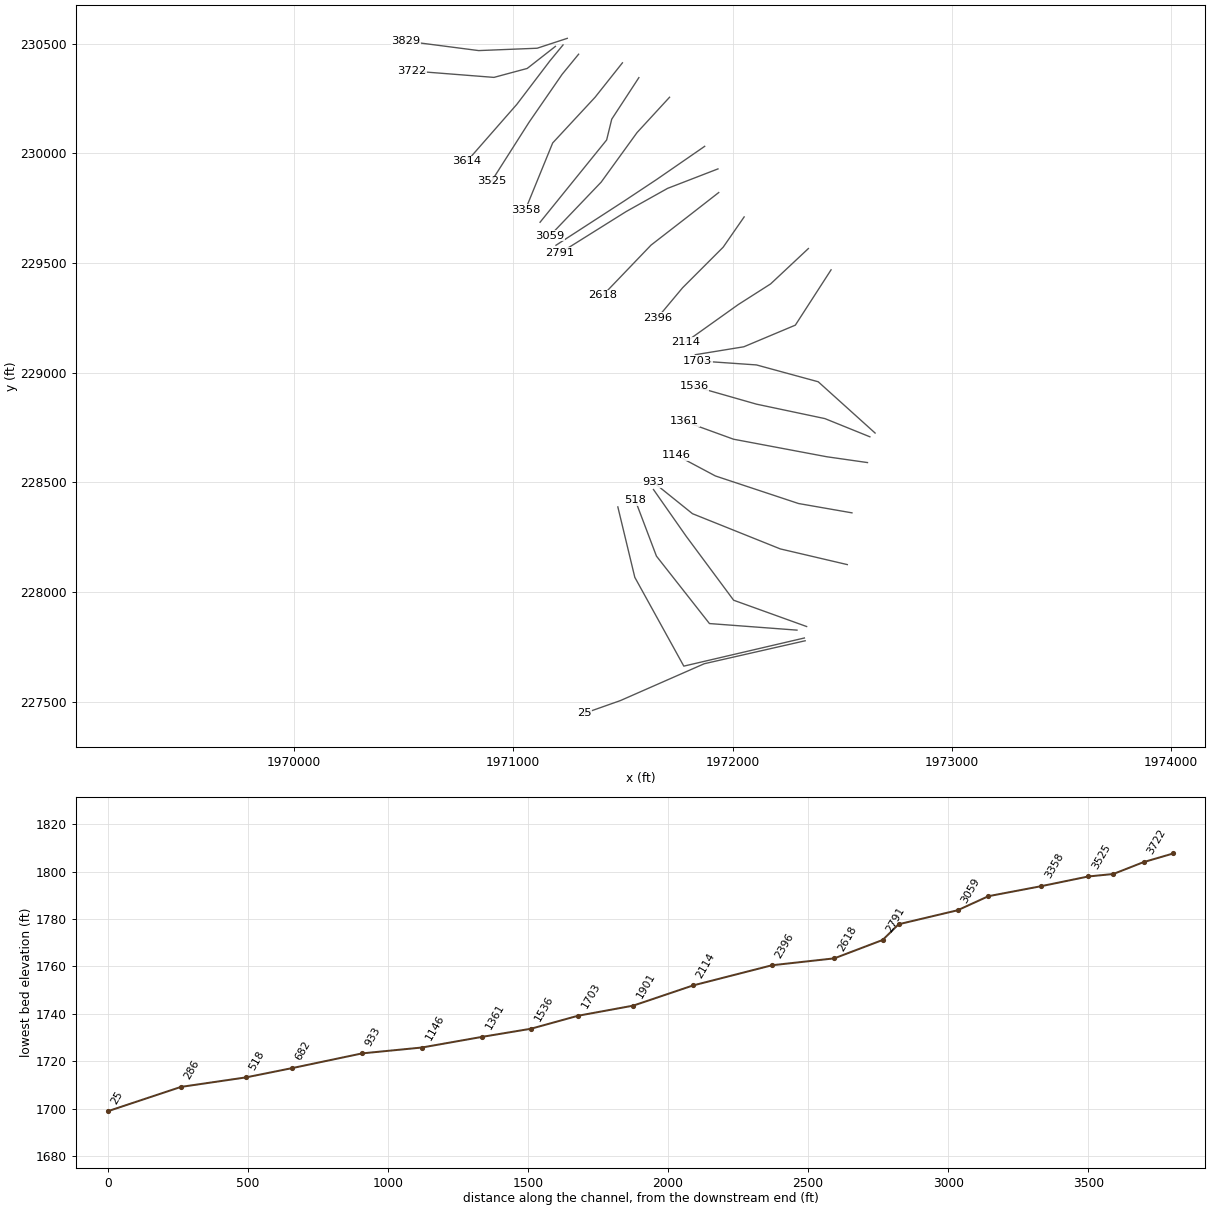
HEC-RAS study PRKRCK.prj: PRKRCK

--- PRKRCK.g01 (geometry) --- (continued)

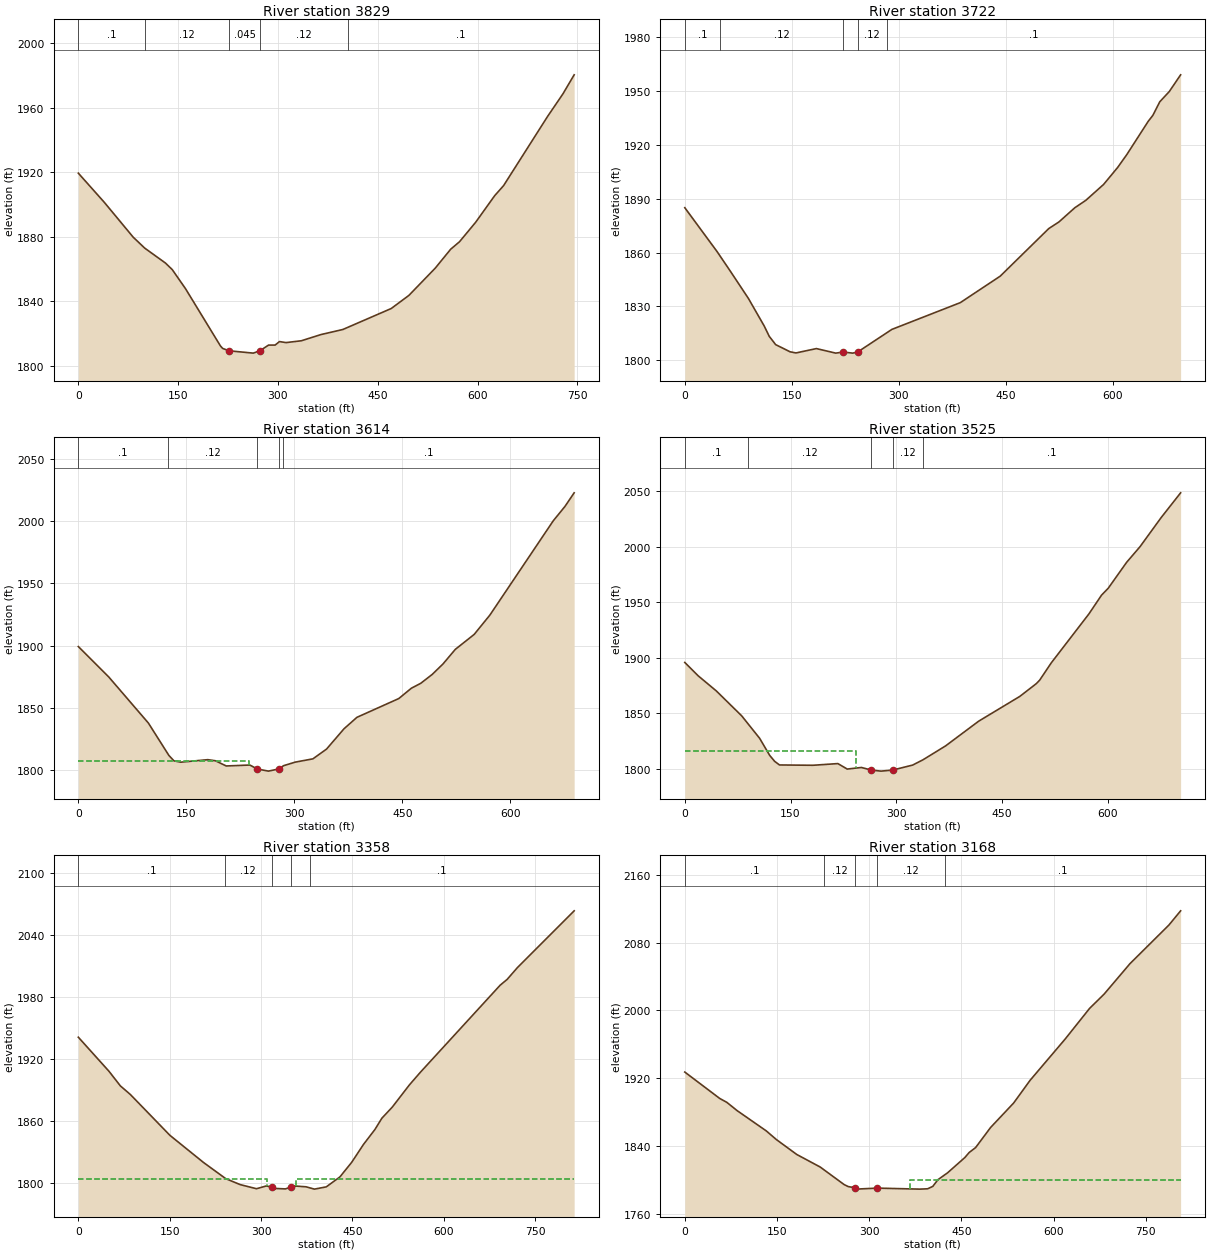
Type RM Length L Ch R = 1 ,3829    ,99.7,106.6,112.1
XS GIS Cut Line= 4
1971246.67027282 230524.995443761971109.14944745230479.871422934
1970842.70284828230469.1276084511970511.79336222230512.102866381
#Sta/Elev= 30
       0 1919.42      39 1901.33    82.5 1879.66    99.8 1872.88   130.9 1863.64
   141.2 1859.52   161.1 1847.69   213.6 1812.14   216.9 1810.62   226.61809.145
   262.9  1807.7  272.761809.145   285.9  1812.7   295.7  1812.7   302.3 1814.87
   312.1 1814.24   335.1 1815.37   364.7 1819.23   397.5 1822.37   470.2 1835.39
   496.7 1843.52   536.4 1860.48   559.5 1872.18   572.8 1876.84   597.1 1888.95
   625.7 1905.46     639 1911.65   705.1 1954.59   728.3 1968.69   745.1 1980.47
#Mann= 5 ,-1 , 0
       0      .1       0     100     .12       0   226.6    .045       0
  272.76     .12       0  404.73      .1       0
Bank Sta=226.6,272.76
XS Rating Curve= 0 ,0
Exp/Cntr(USF)=0,0
Exp/Cntr=0.3,0.1

Type RM Length L Ch R = 1 ,3722    ,89.4,108.1,125.5
XS GIS Cut Line= 4
1971192.57230289230488.3434780921971063.87066392230387.675859499
1970912.23209921230346.8991026011970538.86991886230376.207396622
#Sta/Elev= 30
       0 1884.97    45.2 1860.57    64.2 1849.42    89.2 1834.44   111.4 1819.06
   118.3 1813.41   127.3 1808.77   147.5 1804.78   155.8 1804.13   184.4 1806.56
   211.6 1804.03   221.8 1804.63   235.4 1804.03   242.2 1804.62   242.2 1804.63
   290.3 1817.25   386.1 1832.12   442.1 1846.88   510.1 1873.35   524.3 1877.03
   546.7 1884.96     562 1889.06   586.9 1897.89   606.6 1907.34   619.6  1914.6
   649.4 1932.99     656 1936.36   665.7 1943.93     679  1949.6   694.9 1958.92
#Mann= 5 ,-1 , 0
       0      .1       0      50     .12       0   221.8    .045       0
   242.2     .12       0   283.4      .1       0
Bank Sta=221.8,242.2
XS Rating Curve= 0 ,0
Exp/Cntr(USF)=0,0
Exp/Cntr=0.3,0.1

Type RM Length L Ch R = 1 ,3614    ,88,89.2,90.4
XS GIS Cut Line= 4
1971227.33140676230494.9127632091971167.16604565230421.854824728
 1971016.7526429 230224.168638251970788.98377587229964.168327773
#Sta/Elev= 30
       0 1899.19    42.1 1874.84    97.3 1837.67   125.8 1811.62   132.8 1807.27
   142.2  1806.2   179.8 1808.22   190.4 1807.35   205.4 1803.16   238.2 1803.91
  248.58 1800.75     264 1799.01  278.371800.747     285 1803.36   301.1 1806.22
   325.8 1808.88   344.8 1816.75   369.1  1833.1     387 1842.28   445.1 1857.36
   462.5 1865.65   475.6 1869.63   491.5 1876.75   506.5 1885.17   523.6 1896.91
   549.8 1908.93   571.6 1924.45   659.7 2000.33   675.8 2011.76   688.7  2022.8
#Mann= 5 ,-1 , 0
       0      .1       0  124.64     .12       0  248.58    .045       0
  278.37     .12       0  284.64      .1       0
#XS Ineff= 2 , 0
          237.02 1807.52
Permanent Ineff=
       F       F
Bank Sta=248.58,278.37
XS Rating Curve= 0 ,0
Exp/Cntr(USF)=0,0
Exp/Cntr=0.3,0.1

Type RM Length L Ch R = 1 ,3525    ,171.5,167.2,163.8
XS GIS Cut Line= 4
1971298.33701609230452.6638158061971223.15487056230360.916112785
 1971072.7905795230143.0153181091970900.76363633229872.869303656
#Sta/Elev= 30
       0 1895.81    18.9 1883.85    44.8 1870.15    80.8 1847.71   106.2 1827.53
   120.5 1812.13   127.6 1806.73   134.4 1803.52   181.8 1803.24   217.2 1804.76
   230.5 1799.83   250.5 1801.26   264.81798.923   278.4 1797.97   294.81798.912
   323.4 1803.43   338.1 1808.21     370 1820.65     417 1842.93   475.4 1865.25
   498.7 1876.69   503.5 1879.81   520.1 1895.51   573.5 1939.56   591.4 1956.44
   600.9 1962.67     627 1986.01   646.1 2000.16     676  2026.3   703.6 2048.57
#Mann= 5 ,-1 , 0
       0      .1       0      90     .12       0   264.8    .045       0
   294.8     .12       0  338.62      .1       0
#XS Ineff= 2 , 0
          242.77 1815.75
Permanent Ineff=
       F       F
Bank Sta=264.8,294.8
XS Rating Curve= 0 ,0
Exp/Cntr(USF)=0,0
Exp/Cntr=0.3,0.1

Type RM Length L Ch R = 1 ,3358    ,176.3,189.5,200.1
XS GIS Cut Line= 4
1971498.07553171230413.2597731421971373.44728372230256.400081697
1971180.05862303230047.9700807371971055.43037504229742.845749433
#Sta/Elev= 30
       0 1941.07    50.3  1908.1      69 1893.94    85.4  1885.6   150.5 1845.97
   205.8 1819.62     242 1804.09   265.7  1798.3   292.6 1794.29   308.7 1796.98
   317.7 1795.93   322.8 1794.57   340.1 1794.12     349 1795.87     358 1796.83
   373.9 1796.15   387.8  1793.9   407.2 1796.09   429.6 1805.72     449 1819.93
   468.3 1837.18   487.1 1851.67   498.5 1862.59   515.5 1873.29   543.8 1894.92
   561.5 1906.95   692.7  1991.4   704.3 1997.11     721 2008.42   814.3  2063.5
#Mann= 5 ,-1 , 0
       0      .1       0  240.34     .12       0   317.7    .045       0
     349     .12       0  380.34      .1       0
#XS Ineff= 2 , 0
          310.16 1803.78  358.16          1804.1
Permanent Ineff=
       F       F
Bank Sta=317.7,349
XS Rating Curve= 0 ,0
Exp/Cntr(USF)=0,0
Exp/Cntr=0.3,0.1

Type RM Length L Ch R = 1 ,3168    ,116.5,109.7,95.4
XS GIS Cut Line= 4
1971573.08478999 230345.852975071971449.31604715230156.332087597
1971426.10940786 230061.571643861971122.48921059229686.397642128
#Sta/Elev= 30
       0 1927.49    56.7 1896.47    68.5 1891.76      85 1882.15   132.5 1858.23
     149    1848   182.2 1830.42   220.2  1815.7   259.2 1795.01   265.9 1792.63
   276.61791.316   282.8 1789.81   313.2 1790.84   382.3 1789.65     395 1790.04
   403.4 1792.86   411.8 1800.75   427.6 1808.92   455.6 1826.86   462.5 1832.68
   473.1  1838.6   497.5 1862.26   534.9 1890.98   561.7 1917.75   618.7 1966.29
   658.5 2002.45     682 2019.15   724.2 2055.11   787.5 2100.55   806.6 2117.33
#Mann= 5 ,-1 , 0
       0      .1       0  226.36     .12       0   276.6    .045       0
   313.2     .12       0  423.92      .1       0
#XS Ineff= 2 , 0
                          365.97         1800.28
Permanent Ineff=
       F       F
Bank Sta=276.6,313.2
XS Rating Curve= 0 ,0
Exp/Cntr(USF)=0,0
Exp/Cntr=0.3,0.1

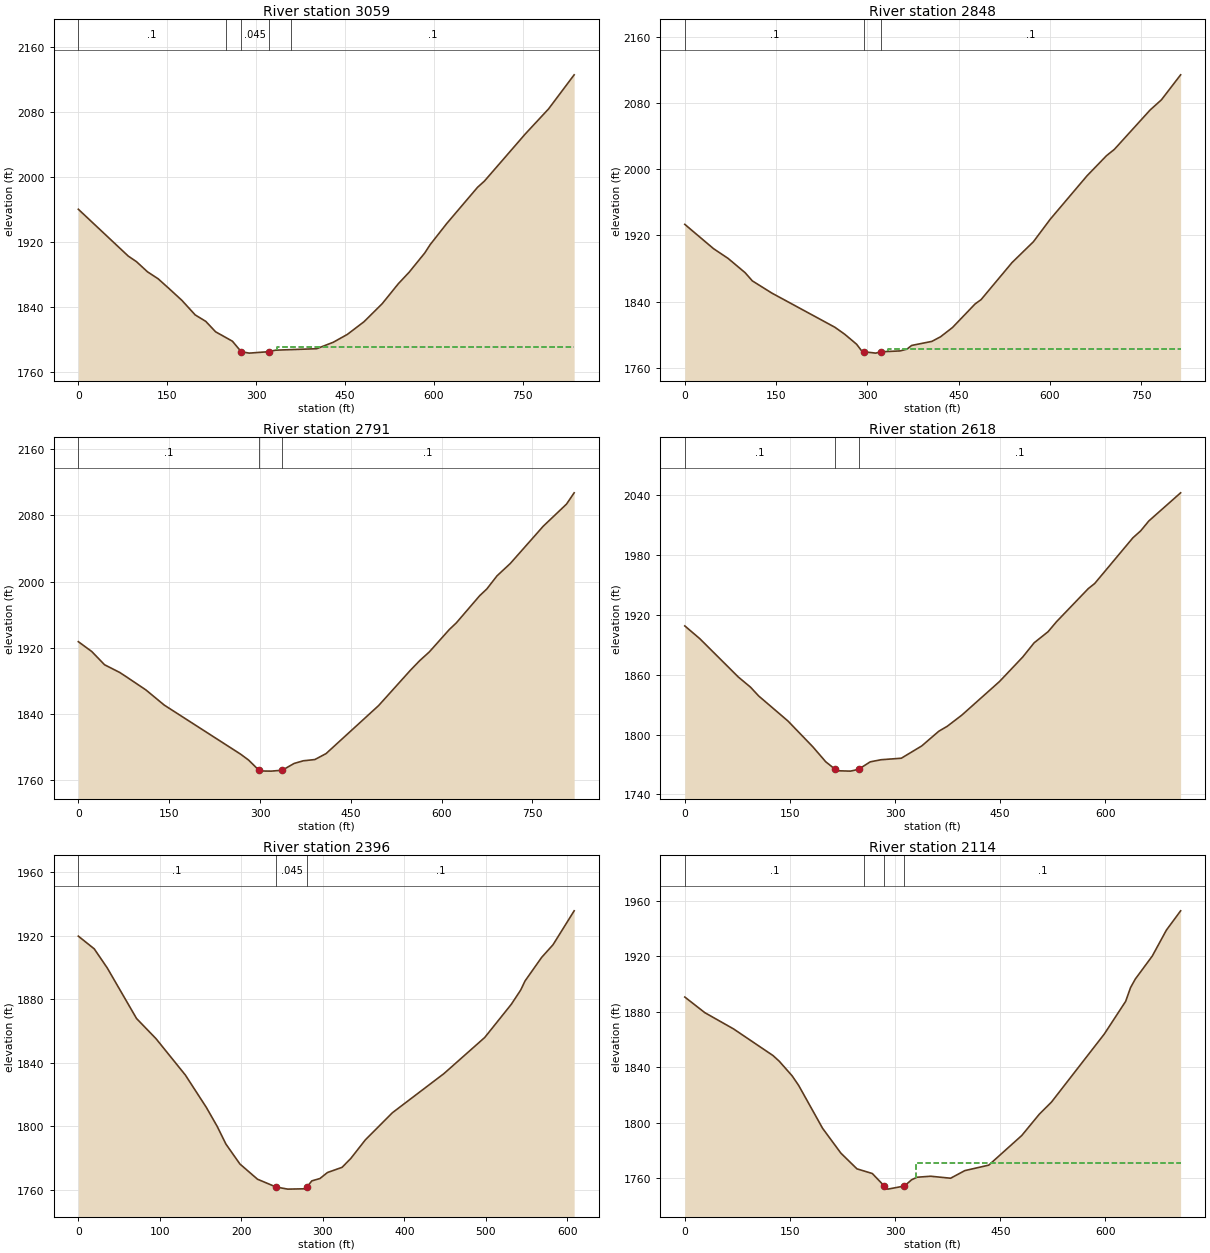
Type RM Length L Ch R = 1 ,3059    ,218.8,210.8,193.8
XS GIS Cut Line= 4
1971712.95182136230256.4000816971971564.68718151 230095.24286446
1971401.38120137229869.6227603271971167.16604565229624.663790125
#Sta/Elev= 30
       0 1960.34    84.2 1902.86    98.1 1895.99   116.7 1883.52   134.7 1874.95
   152.5 1863.33   174.6 1848.58   197.1 1830.66     215  1822.7   231.5 1809.93
   259.9 1798.36   274.8 1785.47   288.2 1783.72  320.991785.472   332.8 1787.34
   402.1 1789.15     430 1797.05   453.8 1806.69     482 1822.33   512.6 1844.41
   539.8 1868.91     558    1883   584.3 1906.59   593.5 1916.89   621.5 1942.85
   673.4 1987.25   685.1 1994.96   754.1 2052.89   793.1 2083.41   836.4 2125.36
#Mann= 5 ,-1 , 0
       0      .1       0  248.98     .12       0   274.8    .045       0
  320.99     .12       0  358.98      .1       0
#XS Ineff= 2 , 0
                          335.72         1791.59
Permanent Ineff=
       F       F
Bank Sta=274.8,320.99
XS Rating Curve= 0 ,0
Exp/Cntr(USF)=0,0
Exp/Cntr=0.5,0.3

Type RM Length L Ch R = 1 ,2848    ,58.4,56.8,56
XS GIS Cut Line= 4
1971873.10402824230032.602217546 1971654.5845111229881.753260551
 1971503.7355541229781.6572236671971194.98862343229581.465149899
#Sta/Elev= 30
       0 1933.42    47.2 1904.04    71.1 1892.29      99 1875.09     111 1865.09
   142.9 1850.41   246.5 1809.09   262.5 1800.76   282.2 1788.58   290.1 1780.94
  294.64 1779.42   313.7 1777.81  321.91 1779.42   353.7 1780.48   364.9 1782.61
   372.7  1787.1   405.8 1791.99     420 1797.51   439.7 1808.72   476.9 1837.26
   486.7 1842.47   537.5 1887.19   572.7 1912.44   600.4 1939.69   660.7 1992.07
   692.7 2016.39   705.6    2024   764.3 2071.56   782.9 2083.87   814.5 2114.13
#Mann= 3 ,-1 , 0
       0      .1       0  294.64    .045       0  321.91      .1       0
#XS Ineff= 2 , 0
          286.11 1779.98  333.36          1783.2
Permanent Ineff=
       F       F
Bank Sta=294.64,321.91
XS Rating Curve= 0 ,0
Exp/Cntr(USF)=0,0
Exp/Cntr=0.5,0.3

Type RM Length L Ch R = 1 ,2791    ,165.8,172.7,175.3
XS GIS Cut Line= 4
 1971933.7255717229929.6865739891971703.92762787229840.868963796
1971515.01398079229735.133713566 1971213.3160668229546.220066489
#Sta/Elev= 30
       0  1927.5    22.2 1915.61    43.3 1899.64    68.4  1890.3    78.5 1885.49
   111.5 1869.29   141.9 1850.92   267.7 1791.81   281.2 1784.54  298.191772.298
   301.4 1771.37   318.8 1771.19  336.761772.297   356.4 1780.47   371.5 1783.67
   390.6 1785.17   409.1 1792.35   495.8 1850.28   548.6 1893.14   563.8 1904.65
   579.6 1915.11   612.6 1942.15   624.3 1950.26   662.7 1982.96   674.6 1991.16
   691.4 2006.98   713.3 2021.88   767.8 2066.96   806.2 2093.65   818.8 2107.24
#Mann= 3 ,-1 , 0
       0      .1       0  298.19    .045       0  336.76      .1       0
#XS Ineff= 2 , 0
          295.32 1772.52  340.36         1772.86
Permanent Ineff=
       F       F
Bank Sta=298.19,336.76
XS Rating Curve= 0 ,0
Exp/Cntr(USF)=0,0
Exp/Cntr=0.5,0.3

Type RM Length L Ch R = 1 ,2618    ,217.9,222.3,225.3
XS GIS Cut Line= 4
1971937.17175764229821.914941162 1971802.4572166229716.962915008
1971628.58147178229582.2483739741971409.27873056229353.546943848
#Sta/Elev= 30
       0 1909.05    21.4 1896.25    76.4 1857.81    93.9 1847.54   105.5 1838.75
   147.1 1813.77   182.7 1787.84   201.1 1772.83  214.711765.208   220.1 1763.76
   236.5 1763.43  247.931765.206   264.6 1772.73     280 1774.85     309 1776.37
   338.1 1788.67   362.5 1803.43   374.5 1808.37   395.5 1819.68   449.1 1853.27
   482.3 1877.87   498.6 1892.14   518.5 1903.27   530.4  1913.2   575.9  1946.5
     585  1951.6   639.5  1997.4   650.7 2004.44   662.2 2014.27   707.6  2042.5
#Mann= 3 ,-1 , 0
       0      .1       0  214.71    .045       0  247.93      .1       0
Bank Sta=214.71,247.93
XS Rating Curve= 0 ,0
Exp/Cntr(USF)=0,0
Exp/Cntr=0.3,0.1

Type RM Length L Ch R = 1 ,2396    ,277,282.3,268.5
XS GIS Cut Line= 4
1972053.08892085229710.6971224021971957.53558361229572.849685065
1971772.69470172229388.0088031821971657.75191258229250.681378256
#Sta/Elev= 30
       0 1919.68    19.5  1911.7    35.5 1899.66    71.4 1867.87    95.4 1855.11
   131.3 1832.29     157 1811.96   170.4 1799.93     181  1788.9   198.2 1776.33
   219.8 1766.75  242.551761.848   256.9 1760.52   277.1 1760.72  280.46 1761.85
   286.4 1765.71   296.4  1767.2   305.6 1770.97   323.5 1774.23   334.2 1779.81
     352 1791.47   385.2 1808.56   448.5 1833.21   498.5 1855.92   531.1 1876.81
   542.7 1885.84   547.9 1891.45   568.3  1906.3   582.3 1914.29   608.2 1935.61
#Mann= 3 ,-1 , 0
       0      .1       0  242.55    .045       0  280.46      .1       0
Bank Sta=242.55,280.46
XS Rating Curve= 0 ,0
Exp/Cntr(USF)=0,0
Exp/Cntr=0.3,0.1

Type RM Length L Ch R = 1 ,2114    ,213.2,213,204.6
XS GIS Cut Line= 4
1972346.01472519229566.5838924591972173.70542852229405.239732849
1972026.45930227229311.2528437561971784.90322677229139.194545582
#Sta/Elev= 30
       0 1890.48    28.6 1879.21    69.5 1867.51   125.8 1848.31   134.8 1844.18
   153.1 1833.67   162.4 1826.79   196.6 1795.82   222.7 1777.91   245.6 1766.61
   267.5 1763.24  284.561754.244   289.6 1751.99  313.35 1754.24   323.5 1758.71
   331.3 1760.57   350.7 1761.28   379.2 1759.85   399.4 1765.33   433.6 1769.28
   480.7 1790.66   505.7 1806.01     523 1814.71   598.4  1863.8   628.9 1887.38
   635.9 1897.33   642.7 1903.49   666.9 1920.06     687 1938.73   707.3 1952.64
#Mann= 4 ,-1 , 0
       0      .1       0  256.06     .12       0  284.56    .045       0
  313.35      .1       0
#XS Ineff= 2 , 0
                          330.08         1770.72
Permanent Ineff=
       F       F
Bank Sta=284.56,313.35
XS Rating Curve= 0 ,0
Exp/Cntr(USF)=0,0
Exp/Cntr=0.3,0.1

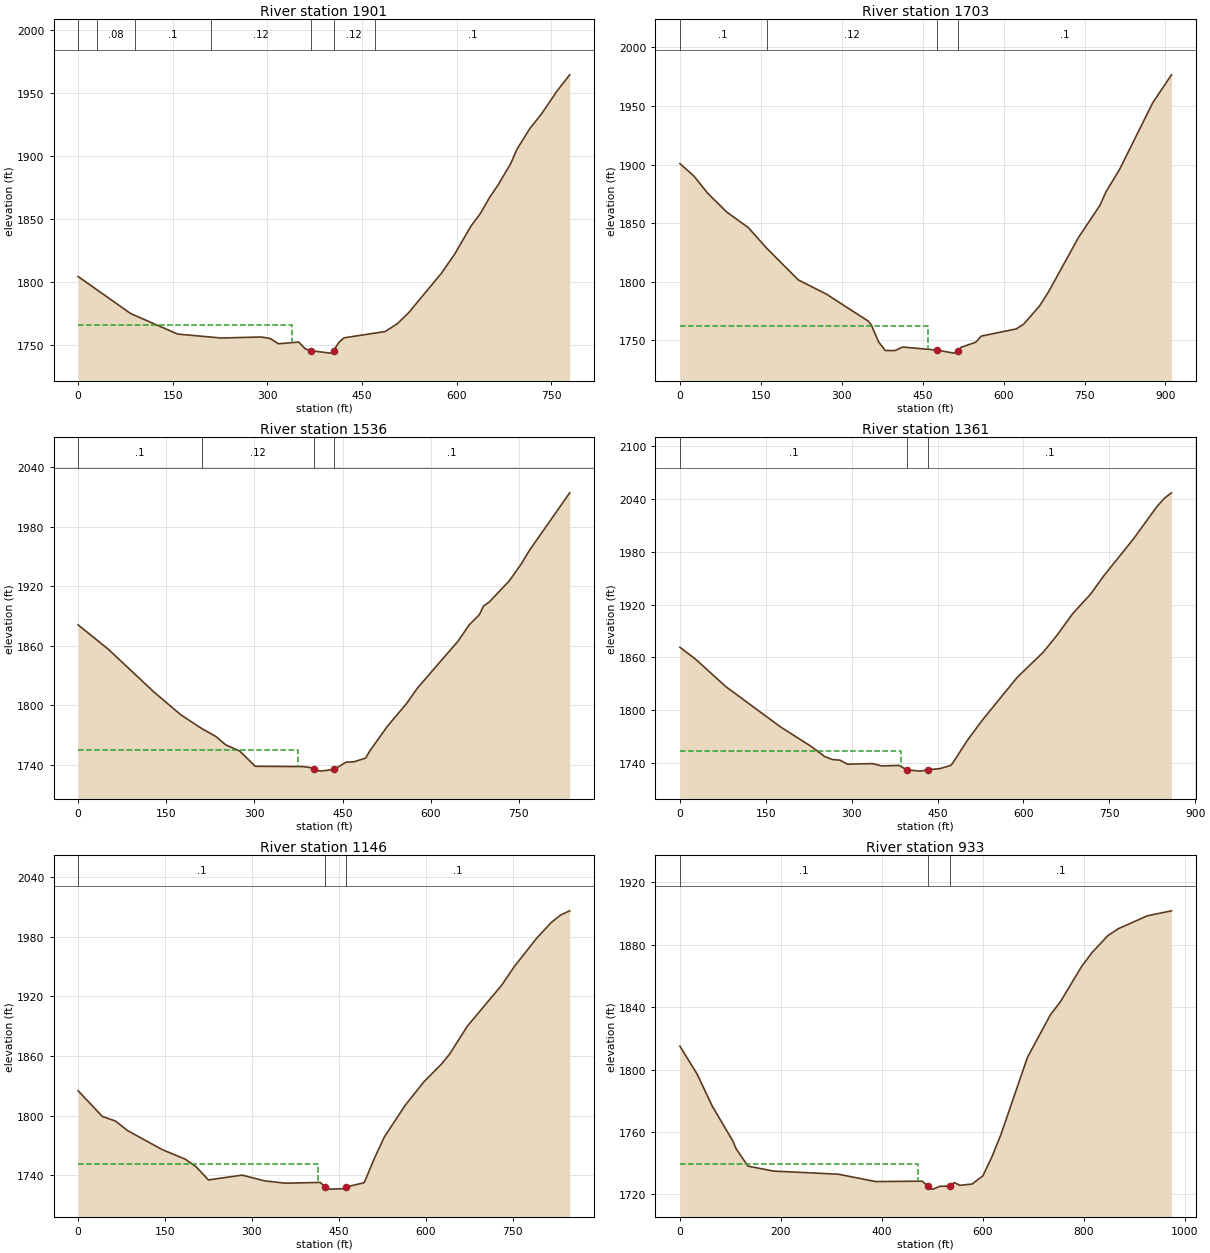
Type RM Length L Ch R = 1 ,1901    ,217.6,197.9,180.1
XS GIS Cut Line= 4
1972449.40030319229469.4641070631972286.48969543229217.265954663
 1972051.5224727229118.5797211151971830.65328333229082.551413629
#Sta/Elev= 30
       0 1804.36    83.4 1774.92   157.6 1758.65   226.7  1755.5   290.4 1756.31
   304.4 1755.11   317.5 1750.93   349.5 1752.27   360.2 1746.74  369.021745.447
   399.3 1743.49   402.9 1743.94   404.71745.443   413.5 1752.21   421.3 1755.64
   486.5 1760.64   506.1 1766.98   523.9  1775.7   575.8 1807.08   596.9 1822.35
   622.3 1844.28   637.8 1854.79   652.2 1867.38   665.6 1877.24   685.5 1894.12
   695.4 1905.53   715.4 1921.68   734.1 1933.47   758.6 1951.61   778.9 1964.63
#Mann= 7 ,-1 , 0
       0      .1       0      30     .08       0      90      .1       0
     210     .12       0  369.02    .045       0   404.7     .12       0
  470.24      .1       0
#XS Ineff= 2 , 0
          339.31 1765.75
Permanent Ineff=
       F       F
Bank Sta=369.02,404.7
XS Rating Curve= 0 ,0
Exp/Cntr(USF)=0,0
Exp/Cntr=0.3,0.1

Type RM Length L Ch R = 1 ,1703    ,165.3,167.2,169
XS GIS Cut Line= 4
1972650.14438131228725.3424952931972390.78644961228959.105894254
1972109.24658955229035.8894924531971839.65084476229054.658816457
#Sta/Elev= 30
       0 1900.82    25.9 1890.24    51.4 1875.59    86.9 1859.46   126.7 1846.28
   160.6 1828.81   219.4 1801.64   272.4 1789.28   349.2 1766.48   354.7 1763.34
   368.3 1748.79   380.8 1741.42   398.9 1741.41   412.8  1744.4     477 1741.76
   507.7  1739.2  515.311740.884   521.3  1744.2   548.5  1748.5   558.7 1753.72
   623.4 1759.83   637.3 1763.93   666.7 1779.44   683.5 1791.58     739 1837.93
   778.5 1865.08   789.5 1876.43   814.7 1895.58   876.5 1952.67   911.2 1976.48
#Mann= 4 ,-1 , 0
       0      .1       0   160.6     .12       0     477    .045       0
  515.31      .1       0
#XS Ineff= 2 , 0
       0   460.1 1762.14               0
Permanent Ineff=
       F       F
Bank Sta=477,515.31
XS Rating Curve= 0 ,0
Exp/Cntr(USF)=0,0
Exp/Cntr=0.3,0.1

Type RM Length L Ch R = 1 ,1536    ,174,174.6,175.2
XS GIS Cut Line= 4
1972626.40894432228708.1703054081972421.20423647 228791.19205744
1972109.48105431228856.9828798051971824.38749072228938.438183686
#Sta/Elev= 30
       0 1880.99    51.1 1856.59     129 1813.42     175 1790.31   210.4 1776.61
   234.4 1768.65   251.2 1760.23   275.1 1753.89   301.5 1738.63     382 1738.31
   395.4 1737.34  401.02 1735.47   412.2 1733.74  436.021735.471   455.8 1742.75
   469.2  1743.1   489.3 1746.85   496.2 1753.95   526.7 1779.19   559.1  1801.9
   577.1 1817.12   646.7  1864.7   665.3 1880.86   682.9 1891.25   689.7 1899.78
   699.8 1904.13   734.3  1925.7   754.5  1942.7   768.2 1956.16   836.5  2013.9
#Mann= 4 ,-1 , 0
       0      .1       0   210.4     .12       0  401.02    .045       0
  436.02      .1       0
#XS Ineff= 2 , 0
       0     375 1754.94               0
Permanent Ineff=
       F       F
Bank Sta=401.02,436.02
XS Rating Curve= 0 ,0
Exp/Cntr(USF)=0,0
Exp/Cntr=0.3,0.1

Type RM Length L Ch R = 1 ,1361    ,218.4,214.7,211
XS GIS Cut Line= 4
1972615.44380726228590.6866940411972429.03647722228617.316312618
1972004.52902815228697.2051683471971780.52694248228778.660472228
#Sta/Elev= 30
       0 1871.34    26.9 1858.04      80 1826.63     176 1780.57   229.3 1758.48
   252.7 1747.04   266.1 1743.56   279.4 1742.83   292.8  1738.2   336.3 1738.87
   352.8 1736.25   382.9 1736.81  396.481731.778   419.6 1730.31  432.511731.779
   454.3 1733.21     473  1736.8   476.4 1739.26     502 1765.25   527.3 1787.58
   589.1 1837.04   633.9  1865.2   658.5 1884.81   686.2 1909.73   717.4 1931.84
   740.2 1952.53     791 1993.64   833.5 2031.76   846.8 2041.31   858.6 2047.15
#Mann= 3 ,-1 , 0
       0      .1       0  396.48    .045       0  432.51      .1       0
#XS Ineff= 2 , 0
          385.39 1753.31
Permanent Ineff=
       F       F
Bank Sta=396.48,432.51
XS Rating Curve= 0 ,0
Exp/Cntr(USF)=0,0
Exp/Cntr=0.3,0.1

Type RM Length L Ch R = 1 ,1146    ,213.4,213,210.6
XS GIS Cut Line= 4
1972544.68289631228361.4050979321972301.01318385228403.950603283
1971921.97140891228529.6532327291971744.05384107228624.413676465
#Sta/Elev= 30
       0 1824.98    41.8 1799.09    64.5 1794.43    85.1 1784.88     145  1765.7
     185 1755.98   203.9 1748.19   224.9 1735.08   282.9 1739.94   321.8 1734.14
   358.1 1731.78   417.7 1732.59  426.711728.056   434.9 1725.82   455.7 1726.16
  462.941728.057   493.7 1732.29   511.3 1756.84   528.3 1778.26   564.3 1810.19
   596.9 1834.14   626.9 1851.78   641.1 1861.97   671.7 1890.08   731.2 1931.59
     753 1950.36   791.8 1979.06   816.7  1994.7     833 2002.24   848.3 2006.33
#Mann= 3 ,-1 , 0
       0      .1       0  426.71    .045       0  462.94      .1       0
#XS Ineff= 2 , 0
          414.37 1751.57
Permanent Ineff=
       F       F
Bank Sta=426.71,462.94
XS Rating Curve= 0 ,0
Exp/Cntr(USF)=0,0
Exp/Cntr=0.3,0.1

Type RM Length L Ch R = 1 ,933     ,259.8,250.9,237.4
XS GIS Cut Line= 4
1972523.41014364228125.4709318961972217.85605975 228197.02473635
1971817.54153214228357.537324719 1971639.6239643228500.644933626
#Sta/Elev= 30
       0 1815.05    33.9 1797.26    64.2 1776.52   104.6 1754.35   111.4 1749.22
   134.7 1738.11   185.5 1734.92   313.6 1732.92   387.8 1728.19   479.7 1728.47
  490.321725.489   493.8 1723.84   500.9 1723.35     515 1725.15   534.3 1725.31
   543.3 1727.54   554.5 1725.78   578.6 1726.61   599.9 1731.83   617.6 1743.86
   635.3 1757.98   688.3 1807.89   733.7  1835.2   753.2 1843.37   795.1 1865.95
   816.1 1875.06   847.5 1885.93   868.4 1890.42   925.9 1898.66   973.4 1901.83
#Mann= 3 ,-1 , 0
       0      .1       0  490.32    .045       0   534.3      .1       0
#XS Ineff= 2 , 0
          471.16 1739.59
Permanent Ineff=
       F       F
Bank Sta=490.32,534.3
XS Rating Curve= 0 ,0
Exp/Cntr(USF)=0,0
Exp/Cntr=0.3,0.1

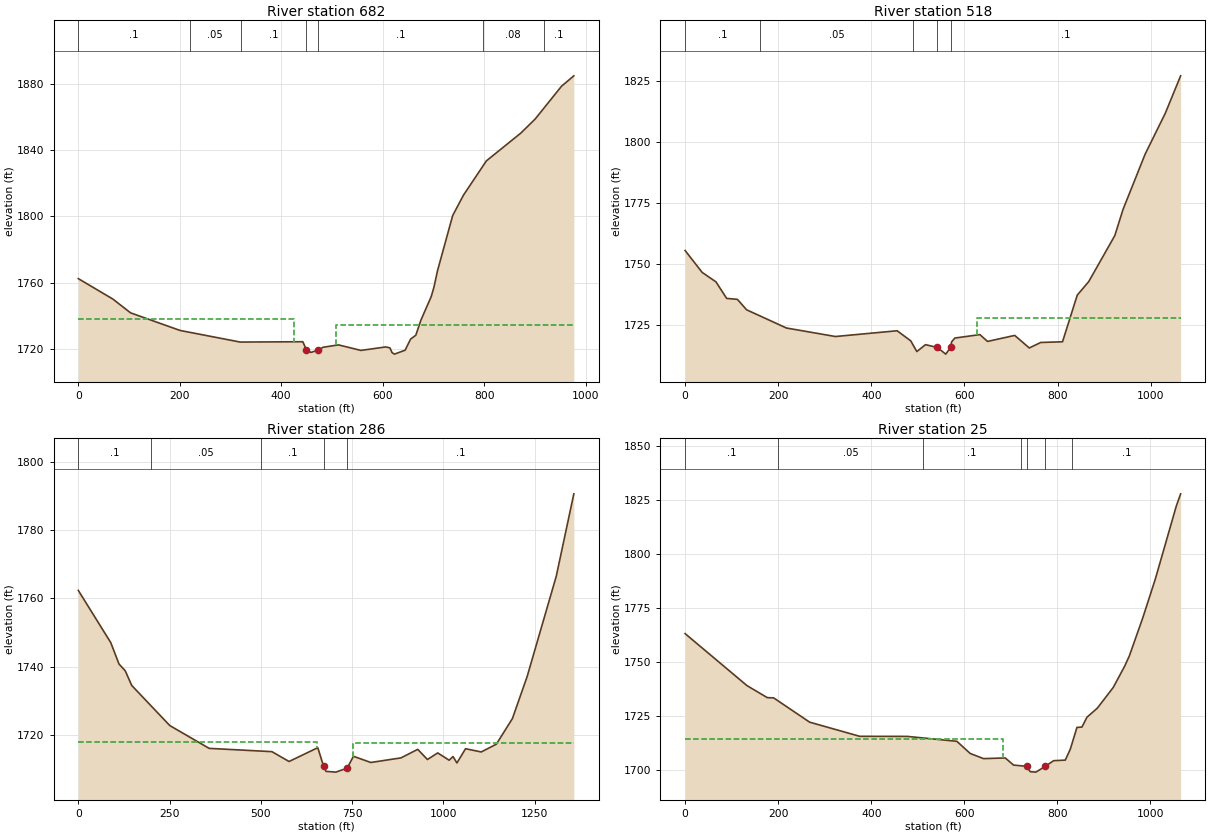
Type RM Length L Ch R = 1 ,682     ,159.8,164.5,162.4
XS GIS Cut Line= 4
1972337.95041804227843.123487295  1972005.128533 227963.02445692
1971788.53323303228255.041334555 1971639.6239643228467.768861309
#Sta/Elev= 30
       0 1762.56    68.1 1750.27     103 1741.97   200.6 1731.37   319.2 1724.38
   442.6 1724.58   449.7 1719.85   458.8 1718.15   473.1 1719.53   482.5 1721.25
     513 1722.68   557.2 1719.35   606.2 1721.45   614.4  1720.9   618.5 1718.09
   623.2 1717.12   644.3 1719.48   655.2 1726.19   665.4 1728.47   675.7 1737.74
   695.7 1751.66   701.2 1757.41   708.3 1767.44   738.2 1800.57   759.4 1812.81
   804.6 1833.45   872.5 1850.16   900.8 1858.63   952.8 1878.39     977 1884.62
#Mann= 7 ,-1 , 0
       0      .1       0     220     .05       0     320      .1       0
   449.7    .045       0   473.1      .1       0  797.34     .08       0
  917.34      .1       0
#XS Ineff= 2 , 0
          425.15 1738.51   508.6         1734.88
Permanent Ineff=
       F       F
Bank Sta=449.7,473.1
XS Rating Curve= 0 ,0
Exp/Cntr(USF)=0,0
Exp/Cntr=0.3,0.1

Type RM Length L Ch R = 1 ,518     ,241.6,231.9,207.7
XS GIS Cut Line= 4
1972294.05119206227826.6854511371971894.89699641227856.660693543
1971653.16117055228164.1486640331971556.46684021228419.421696138
#Sta/Elev= 30
       0 1755.55    36.7  1746.6    66.3 1742.75    89.3 1735.98   112.3  1735.6
   132.1 1731.33   217.6 1723.89   322.9 1720.41   455.5 1722.76   484.7 1718.63
   497.7 1714.26   516.4 1717.08   542.1 1715.92   559.8 1713.21   570.2 1715.96
   572.5 1718.25   579.5 1719.79   633.2 1721.19   649.6  1718.4     708 1720.86
   739.3 1715.73   763.8 1717.97   810.7 1718.26   842.3 1737.32   866.9 1742.83
     923 1761.66   940.5 1772.27   988.1 1794.94  1031.4 1811.65  1064.4 1826.97
#Mann= 5 ,-1 , 0
       0      .1       0     160     .05       0  490.28      .1       0
   542.1    .045       0   570.2      .1       0
#XS Ineff= 2 , 0
                          627.51         1727.81
Permanent Ineff=
       F       F
Bank Sta=542.1,570.2
XS Rating Curve= 0 ,0
Exp/Cntr(USF)=0,0
Exp/Cntr=0.3,0.1

Type RM Length L Ch R = 1 ,286     ,210.3,261.2,314.8
XS GIS Cut Line= 4
1972327.67605307227790.864106428 1971777.9596231227662.553780776
 1971554.5329536 228067.454333691971477.17748933228388.479510428
#Sta/Elev= 30
       0 1762.36    88.9 1747.09   111.4 1740.84   128.7 1738.82   146.2 1734.57
   250.6 1722.82   358.4 1716.15   530.3 1715.19   577.2 1712.31   655.9 1716.35
   672.1 1710.86   678.5 1709.42   705.1  1709.2   736.5 1710.36   753.5 1713.84
   801.1 1712.02   883.8 1713.37   929.7 1715.87   956.2 1712.89   984.4 1714.82
  1015.6 1712.69  1026.3 1713.75    1037 1711.88  1060.6 1716.05  1103.6  1715.1
    1145 1717.38  1188.9 1724.86  1229.3 1737.16    1309 1766.48  1357.2 1790.62
#Mann= 5 ,-1 , 0
       0      .1       0     200     .05       0     500      .1       0
   672.1    .045       0   736.5      .1       0
#XS Ineff= 2 , 0
          653.87 1717.88   752.4          1717.8
Permanent Ineff=
       F       F
Bank Sta=672.1,736.5
XS Rating Curve= 0 ,0
Exp/Cntr(USF)=0,0
Exp/Cntr=0.3,0.1

Type RM Length L Ch R = 1 ,25      ,,,
XS GIS Cut Line= 4
1972331.37298777227778.1858683411971871.29064327227673.511049223
1971489.10583859 227505.544479011971323.57356649227447.121324154
#Sta/Elev= 30
       0 1763.01     133 1738.95   176.7 1733.39   190.2 1733.29   267.6 1722.05
   375.2 1715.51   477.4 1715.47     584 1713.19   612.6 1707.57   641.3 1705.19
   687.9  1705.5   705.8  1702.2   733.8 1701.63   741.6 1699.14   753.8 1698.94
   773.9 1701.61   791.8 1704.23   816.9  1704.5   827.7 1709.55     842 1719.62
   852.7 1719.78   863.5 1724.34   885.7 1728.52   919.9 1738.08   944.3 1747.86
   954.7 1752.76   983.3 1770.21  1010.4 1788.25  1055.6 1822.12  1064.8 1827.68
#Mann= 7 ,-1 , 0
       0      .1       0     200     .05       0  511.84      .1       0
  721.84     .04       0   733.8    .045       0   773.9     .04       0
  831.84      .1       0
#XS Ineff= 2 , 0
          682.52 1714.04
Permanent Ineff=
       F       F
Bank Sta=733.8,773.9
XS Rating Curve= 0 ,0
Exp/Cntr(USF)=0,0
Exp/Cntr=0.3,0.1
LCMann Table=0

Chan Stop Cuts=-1
Use User Specified Reach Order=0
Composite Channel Slope=5